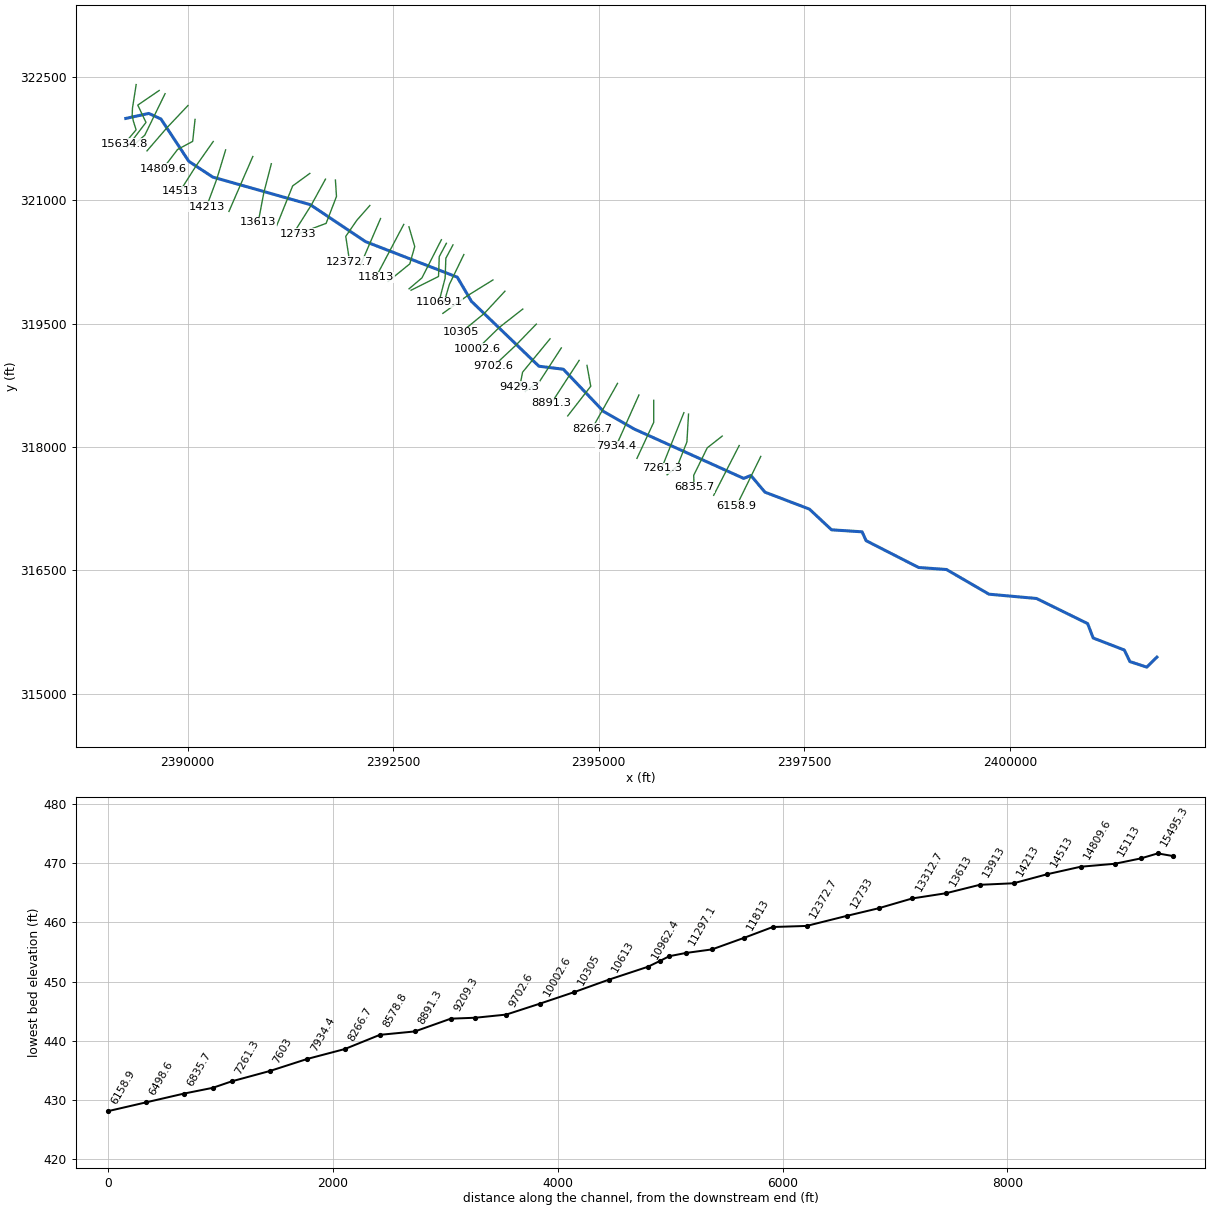
--- MIDDLECRK1.prj (project) ---

Proj Title=MIDDLECRK1
Current Plan=p01
Default Exp/Contr=0,0
English Units
Geom File=g01
Flow File=f01
Plan File=p01
BEGIN DESCRIPTION:
END DESCRIPTION:
DSS Export Rating Curves= 0
DSS Export Rating Curve Sorted= 0
DSS Export Volume Flow Curves= 0
DXF OffsetX= 0
DXF OffsetY= 0
DXF ScaleX= 0
DXF ScaleY= 0

--- MIDDLECRK1.p01 (plan) ---

Plan Title=Floodplain
Program Version=4.00
Geom File=g01
Flow File=f01
K Sum by GR=0
Std Step Tol=0.01
Critical Tol=0.01
Num of Std Step Trials=20
Max Error Tol=0.3
Flow Tol Ratio=0.001
Split Flow NTrial=30
Split Flow Tol=0.02
Split Flow Ratio=0.02
Log Output Level=0
Friction Slope Method=1
Unsteady Friction Slope Method=2
Unsteady Bridges Friction Slope Method=1
Global Log Level=0
CheckData=False
Run HTab=0
Run UNet=0
Run PostProcess=0
UNET Theta=0
UNET Theta Warmup=0
UNET ZTol=0
UNET ZSATol=0
UNET MxIter=0
UNET MaxInSteps=0
UNET DtIC=0
UNET DtMin=0
UNET MaxCRTS=0
UNET WFStab=0
UNET SFStab=0
UNET WFX=0
UNET SFX=0
UNET DSS MLevel=0
UNET DZMax Abort=0
UNET Convert EG Bridges=0
UNET Use Existing IB Tables=0
UNET Froude Limit=0
UNET Froude Power=0
Write IC File=0
Echo Input=False
Echo Output=False
Write Detailed=0

--- MIDDLECRK1.f01 (steady flow) ---

Flow Title=NFF Regression Equation
Program Version=5.03
Number of Profiles= 1
Profile Names=P100yr
River Rch & RM=MIDDLECRK1,Main            ,15634.8
2711.085
River Rch & RM=MIDDLECRK1,Main            ,457.8
2972.228
River Rch & RM=MIDDLECRK1,Main            ,225.1
  3323.3
Boundary for River Rch & Prof#=MIDDLECRK1,Main            , 1
Up Type= 0
Dn Type= 3
Dn Slope=0.005939
Set Internal Change=MIDDLECRK1      ,Main            ,15634.8 , 1 , 3 ,485.1
DSS Import GetInterval= 0
DSS Import GetPeak= 0
DSS Import FillOption= 0

--- MIDDLECRK1.g01 (geometry) ---

Geom Title=USGS 10m DEM
Program Version=5.03

River Reach=MIDDLECRK1      ,Main
Reach XY= 30
     2389248.036      321995.927      2389527.55      322056.691
      2389675.12      321988.983     2390013.661      321475.094
     2390305.328      321282.385     2391491.092      320947.316
     2392162.967      320497.663     2393279.286      320065.371
     2393451.161      319771.969     2394272.342      318982.038
     2394569.217       318945.58       2395058.8      318431.691
     2395432.064      318218.149     2396763.661      317617.455
     2396850.467      317653.913     2397020.606      317450.788
     2397562.273      317244.191      2397831.37      316992.455
     2398202.898      316968.149     2398251.509       316860.51
     2398890.398      316534.121     2399228.939      316509.816
       2399746.3      316209.469     2400324.425      316157.385
     2400945.953       315851.83     2401013.661      315676.482
     2401392.134      315530.649     2401459.842      315390.024
     2401664.703      315322.316     2401787.967      315443.843

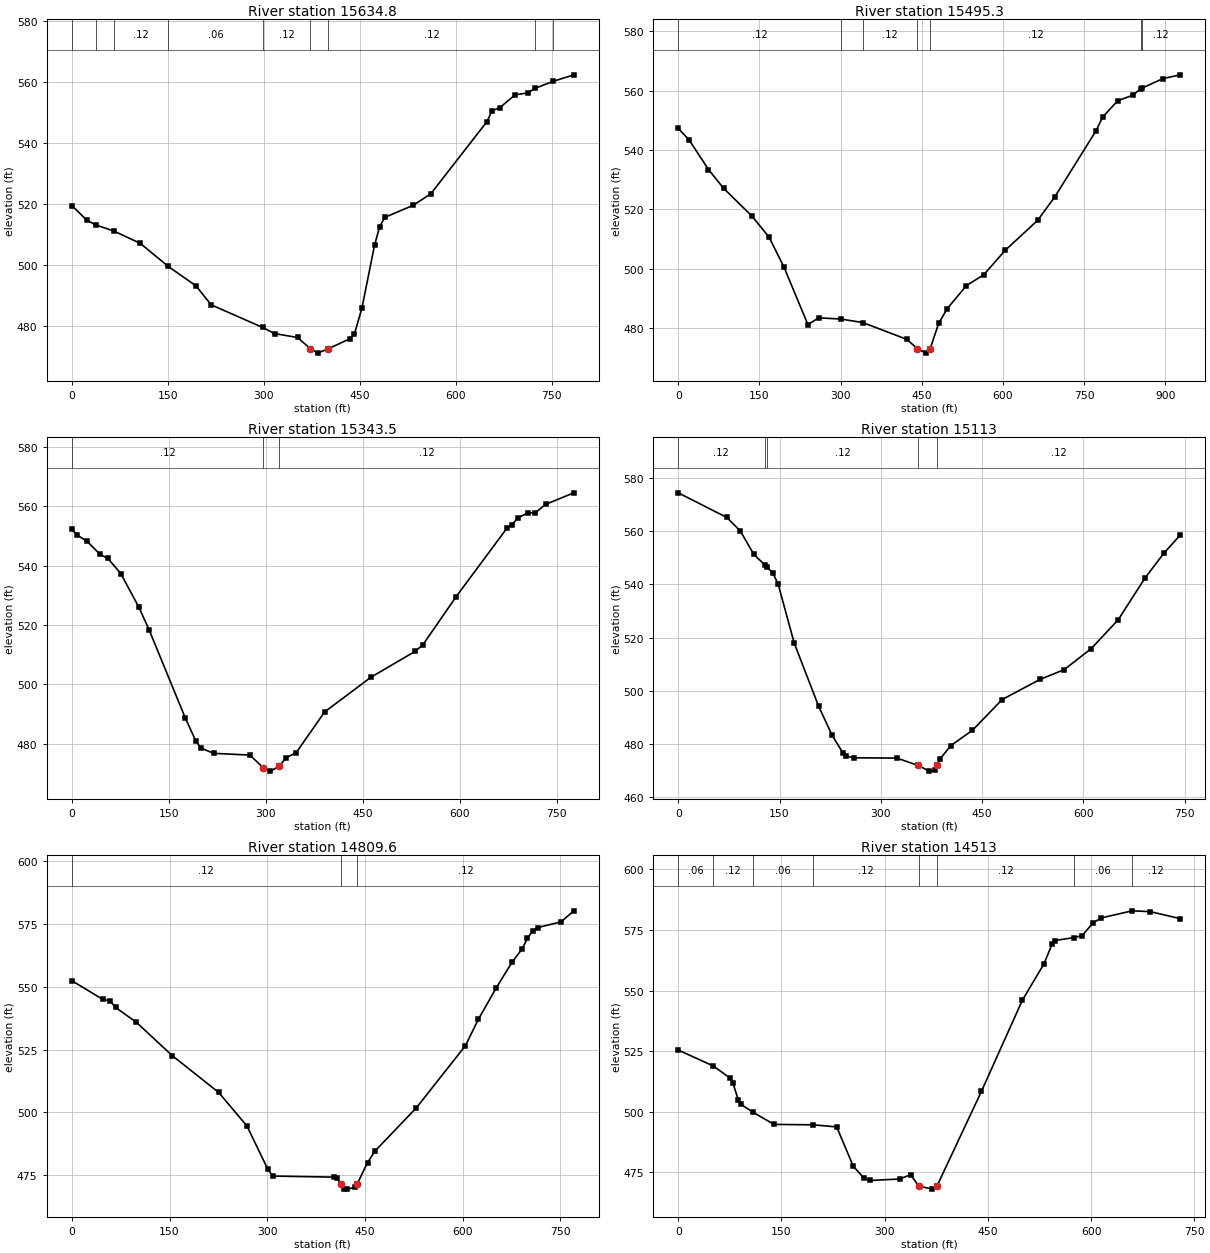
Type RM Length L Ch R = 1 ,15634.8 ,132,139.5,145.4
XS GIS Cut Line= 6
      2389373.98      322407.687     2389329.184      322122.065
     2389325.279      322034.492     2389339.681      321963.344
     2389373.155      321856.895      2389228.58      321686.116
#Sta/Elev= 30
       0  519.49    23.8  514.64   37.31513.1746   66.58511.0594   106.9  507.13
  150.85499.5401   194.1  493.21   217.8  486.98   298.3 479.571     317  477.56
   352.9  476.28   372.8  472.64   384.4  471.16   400.8  472.59   434.1  475.81
   441.7   477.4   453.4  485.84   473.3  506.59   481.2  512.53   489.2  515.61
   533.1  519.52     561   523.3   648.9  546.96   656.8  550.54   668.8  551.49
   692.8  555.73   712.8  556.38  724.01557.8517  751.81560.1315   784.7  562.29
#Mann= 9 ,-1 , 0
       0     .12       0   37.31     .06       0   66.58     .12       0
  150.85     .06       0   298.3     .12       0   372.8    .045       0
   400.8     .12       0  724.01     .06       0  751.81     .12       0
Bank Sta=372.8,400.8
XS Rating Curve= 0 ,0
Exp/Cntr=0.3,0.1

Type RM Length L Ch R = 1 ,15495.3 ,173,151.8,130.8
XS GIS Cut Line= 4
     2389653.964      322335.946     2389393.547      322157.994
     2389493.373      321947.491     2389263.339      321645.842
#Sta/Elev= 30
       0  547.32      20  543.45    55.9  533.46    83.8  527.14   135.8  517.85
   167.7  510.73   195.6   500.5   239.6  481.22   259.5  483.51  300.53483.0987
   341.1481.9133     422  476.28   441.8  473.16   457.6  471.62   465.5   473.1
   481.3  481.68     497   486.6   532.6  494.37   564.4     498   604.3  506.27
   664.2  516.35   696.1  524.34     772   546.5     784  551.08   811.9   556.6
   839.9  558.49  855.07560.7228  857.45560.9213   895.8  564.09   927.7  565.35
#Mann= 7 ,-1 , 0
       0     .12       0  300.53     .06       0   341.1     .12       0
   441.8    .045       0   465.5     .12       0  855.07     .06       0
  857.45     .12       0
Bank Sta=441.8,465.5
XS Rating Curve= 0 ,0
Exp/Cntr=0.3,0.1

Type RM Length L Ch R = 1 ,15343.5 ,237.1,230.5,223.5
XS GIS Cut Line= 3
     2389725.578      322296.883     2389478.183      321791.241
     2389317.592      321650.182
#Sta/Elev= 30
       0  552.22       8  550.33      24  548.13    43.9  543.75    55.9  542.42
    75.8  537.33   103.8  525.99   119.8  518.28   175.7  488.62   191.6  481.08
   199.6  478.54   219.6  476.76   275.5  476.18   295.9471.9725   307.4  470.77
   320.9472.3925   331.4  475.24   347.3  477.03   391.2  490.72   463.1  502.44
     531  511.09     543  513.28   594.6  529.54   673.8  552.79   681.7  553.82
   689.6  556.06   705.4  557.74   717.3  557.83   733.1  560.64   776.7  564.52
#Mann= 3 ,-1 , 0
       0     .12       0   295.9    .045       0   320.9     .12       0
Bank Sta=295.9,320.9
XS Rating Curve= 0 ,0
Exp/Cntr=0.3,0.1

Type RM Length L Ch R = 1 ,15113   ,310.8,303.4,294.9
XS GIS Cut Line= 3
     2390003.973      322153.034      2389751.38      321885.961
     2389505.629      321601.653
#Sta/Elev= 30
       0   574.4    71.9  565.15    91.9  560.08   111.9  551.29  127.73547.4338
   131.3546.4975   139.8  544.42   147.8  540.21   171.8  517.92   207.8  494.27
   227.8  483.34   243.7  476.77   247.7  475.59   259.7  474.87   323.6  474.77
   355.1472.0187   371.6  469.87   379.6  470.19   383.6  471.99   387.6  474.42
   403.6  479.47   435.6  485.19   479.5  496.74   535.5   504.3   571.5  507.99
   611.5  515.89   651.4  526.72   691.4   542.5   719.4  551.83   743.4  558.54
#Mann= 5 ,-1 , 0
       0     .12       0  127.73     .06       0   131.3     .12       0
   355.1    .045       0   383.6     .12       0
Bank Sta=355.1,383.6
XS Rating Curve= 0 ,0
Exp/Cntr=0.3,0.1

Type RM Length L Ch R = 1 ,14809.6 ,286.1,296.6,308.1
XS GIS Cut Line= 4
     2390090.162      321984.383     2390061.192      321717.004
     2389877.527      321618.107     2389699.537      321385.425
#Sta/Elev= 30
       0  552.45    47.5     545    59.3  544.28    67.2  541.76    98.9  535.91
   154.2  522.57   225.4  507.91   268.9  494.51   300.4  477.54   308.3  474.58
   402.8  474.15   406.7  473.96  412.47471.5596   418.5   469.5   422.4  469.37
   434.2  470.04   438.2  471.53   453.9  479.97   465.7  484.64     529  501.83
   604.2  526.57     624  537.08   651.7   549.7   675.5  559.74   691.3  565.15
   699.2   569.3   707.2  572.29   715.1  573.61   750.7  575.87   770.5  580.28
#Mann= 3 ,-1 , 0
       0     .12       0  412.47    .045       0   438.2     .12       0
Bank Sta=412.47,438.2
XS Rating Curve= 0 ,0
Exp/Cntr=0.3,0.1

Type RM Length L Ch R = 1 ,14513   ,292.8,300,304.7
XS GIS Cut Line= 3
     2390311.301       321715.37     2390100.922      321416.646
     2389905.418      321109.393
#Sta/Elev= 30
       0  525.47    50.7518.9554    75.5  513.89    79.4  511.96    87.4  504.79
    91.3  503.05  108.52499.8554     139  494.81  196.04 494.636   230.3  493.78
   254.2  477.63   270.1  472.57     278  471.67   321.7  472.28   337.6  474.05
   349.5  469.39   369.3  468.11  375.83469.2652   440.6  508.44     500     546
   531.6   561.1   543.5  569.35   547.5  570.66  575.23571.8809     587  572.66
   602.9     578   614.8  579.97  659.48582.9052     686  582.57   729.6  579.67
#Mann= 8 ,-1 , 0
       0     .06       0    50.7     .12       0  108.52     .06       0
  196.04     .12       0   349.5    .045       0  375.83     .12       0
  575.23     .06       0  659.48     .12       0
Bank Sta=349.5,375.83
XS Rating Curve= 0 ,0
Exp/Cntr=0.3,0.1

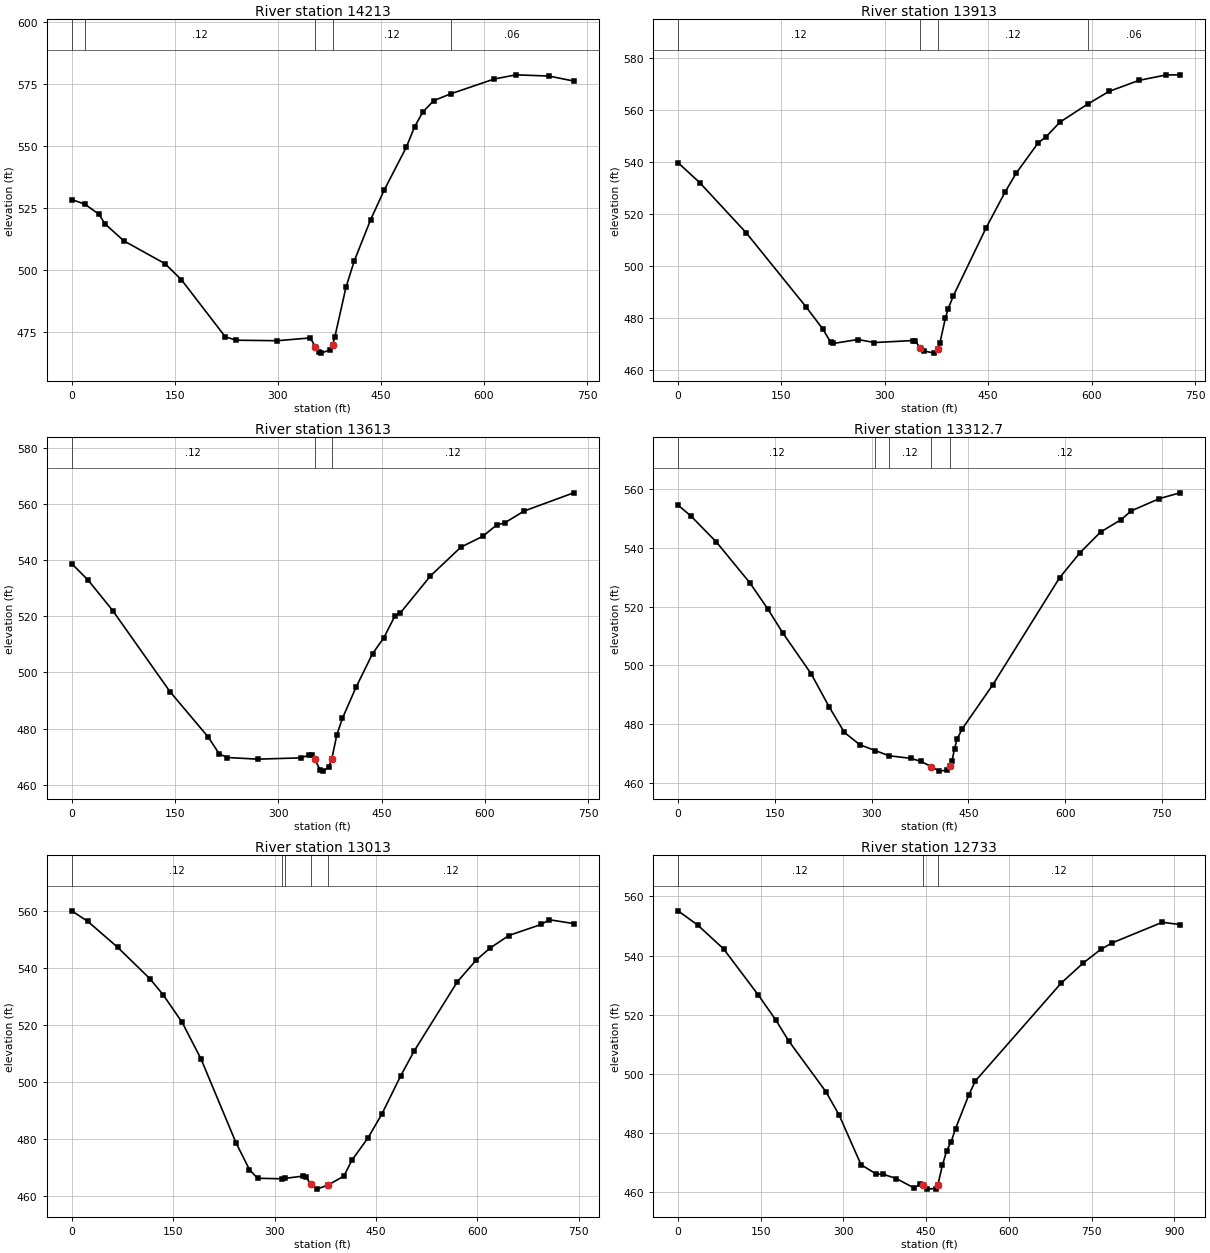
Type RM Length L Ch R = 1 ,14213   ,302.6,300,298.8
XS GIS Cut Line= 3
      2390461.87      321613.402     2390355.719      321261.914
     2390228.874      320921.379
#Sta/Elev= 30
       0  528.41   18.87526.5869    39.9  522.44    47.9  518.74    75.8  511.79
   135.7   502.6   159.6  496.14   223.5  473.14   239.5  471.78   299.3  471.58
   347.2   472.7   354.7469.0675   359.2  466.99   363.2  466.58   375.2  467.83
   379.7469.8426   383.1  473.26   399.1  493.01   411.1  503.59     435  520.26
     455  532.33     487  549.47     499  557.67   510.9  563.62   526.9  568.25
  551.47570.9682   614.8  576.94   646.7  578.64   694.6  578.15   730.6  576.14
#Mann= 5 ,-1 , 0
       0     .06       0   18.87     .12       0   354.7    .045       0
   379.7     .12       0  551.47     .06       0
Bank Sta=354.7,379.7
XS Rating Curve= 0 ,0
Exp/Cntr=0.3,0.1

Type RM Length L Ch R = 1 ,13913   ,296.5,300,305
XS GIS Cut Line= 3
     2390792.454      321532.696     2390647.231      321198.908
     2390502.392      320864.949
#Sta/Elev= 30
       0  539.63    31.6  531.91    98.9  512.64     186  484.02   209.7  475.73
   221.6  470.43   225.5  470.05   261.1  471.56   284.9  470.39   340.3  471.16
   344.2   470.9   351.5468.3646   356.1  467.18   371.9  466.32   376.5467.7385
   379.8  470.15   387.8  479.76   391.7   483.3   399.6  488.48   447.1  514.65
   474.8   528.5   490.6  535.61   522.3   547.2   534.2  549.68   553.9   555.2
  594.61562.2481   625.2  567.06   668.7  571.31   708.2   573.4     728  573.44
#Mann= 4 ,-1 , 0
       0     .12       0   351.5    .045       0   376.5     .12       0
  594.61     .06       0
Bank Sta=351.5,376.5
XS Rating Curve= 0 ,0
Exp/Cntr=0.3,0.1

Type RM Length L Ch R = 1 ,13613   ,303.2,300.3,295.9
XS GIS Cut Line= 3
     2391017.868      321444.655     2390926.251      321091.374
     2390858.382      320733.931
#Sta/Elev= 30
       0  538.69    23.8  532.84    59.5  522.01   142.8  493.12   198.4  476.95
   214.2  471.01   226.1  469.74   269.8  469.16   333.2  469.62   345.1  470.71
   349.1  470.53   352.5469.1615     361  465.25     365   464.9     373  466.29
   377.5469.1613     385  477.87     393  483.67   412.9  494.79   436.9  506.74
   452.9  512.23   468.9  519.92   476.9  521.11   520.9  534.35   564.9  544.55
   596.9  548.46   616.8  552.42   628.8  553.24   656.8  557.42   728.8  563.91
#Mann= 3 ,-1 , 0
       0     .12       0   352.5    .045       0   377.5     .12       0
Bank Sta=352.5,377.5
XS Rating Curve= 0 ,0
Exp/Cntr=0.3,0.1

Type RM Length L Ch R = 1 ,13312.7 ,302.7,299.7,295.1
XS GIS Cut Line= 3
     2391485.561      321326.831     2391277.228      321174.921
     2391083.209      320692.358
#Sta/Elev= 30
       0   554.5    19.8  550.84    59.5  541.94   111.1  528.13   138.8   519.3
   162.6  510.96   206.3  497.14     234     486   257.8  477.19   281.7  473.01
  305.79471.0028  327.13469.2505   361.1  468.36   376.9   467.3   392.8  465.51
   404.7  464.02   416.6  464.33   421.4  465.76   424.6  467.42   428.6  471.67
   432.5  474.88   440.5   478.4   488.1  493.45   591.3  529.76   623.1  538.32
   654.9  545.33   686.6  549.53   702.5  552.54   746.2  556.72   777.9  558.68
#Mann= 5 ,-1 , 0
       0     .12       0  305.79     .06       0  327.13     .12       0
   392.8    .045       0   421.4     .12       0
Bank Sta=392.8,421.4
XS Rating Curve= 0 ,0
Exp/Cntr=0.3,0.1

Type RM Length L Ch R = 1 ,13013   ,274.2,280,285.3
XS GIS Cut Line= 3
     2391676.246      321257.263     2391500.152      320935.992
     2391299.404      320618.294
#Sta/Elev= 30
       0   559.9    23.9  556.16    67.7  547.15   115.5  536.12   135.4   530.4
   163.3  520.78   191.2  507.95   242.9   478.6   262.8  469.19   274.8  466.17
  310.36465.9866  314.95 466.127   342.5  466.94   346.5   466.5   353.9 464.025
   362.4  462.36   378.9 463.785   402.4  466.91   414.3   472.5   438.3   480.4
   458.3  488.54   486.3  501.99   506.3  510.75   570.3  535.07   598.2  542.64
   618.2  546.78   646.2  551.24   694.2  555.13   706.2  556.78   742.2  555.43
#Mann= 5 ,-1 , 0
       0     .12       0  310.36     .06       0  314.95     .12       0
   353.9    .045       0   378.9     .12       0
Bank Sta=353.9,378.9
XS Rating Curve= 0 ,0
Exp/Cntr=0.3,0.1

Type RM Length L Ch R = 1 ,12733   ,364,360.3,353.4
XS GIS Cut Line= 4
     2391797.193       321246.97     2391810.188      321046.827
     2391684.346      320719.626     2391347.974      320593.758
#Sta/Elev= 30
       0  555.12    35.4  550.36    82.6  542.27   145.5  526.71     177  518.33
   200.6   511.2   268.3  493.99   292.2  486.13     332  469.32   359.9  466.17
   371.9  466.12   395.8  464.68   427.6  461.54   439.6  462.68   443.6  462.46
   451.5  461.09   467.3  461.29   471.5  462.62   479.4   469.1   487.4  474.09
   495.4   477.1   503.3  481.52   527.2   492.8   539.2   497.6   694.8  530.67
   734.7  537.44   766.6  542.06   786.6  544.22   878.4  551.25   910.3  550.48
#Mann= 3 ,-1 , 0
       0     .12       0   443.6    .045       0   471.5     .12       0
Bank Sta=443.6,471.5
XS Rating Curve= 0 ,0
Exp/Cntr=0.3,0.1

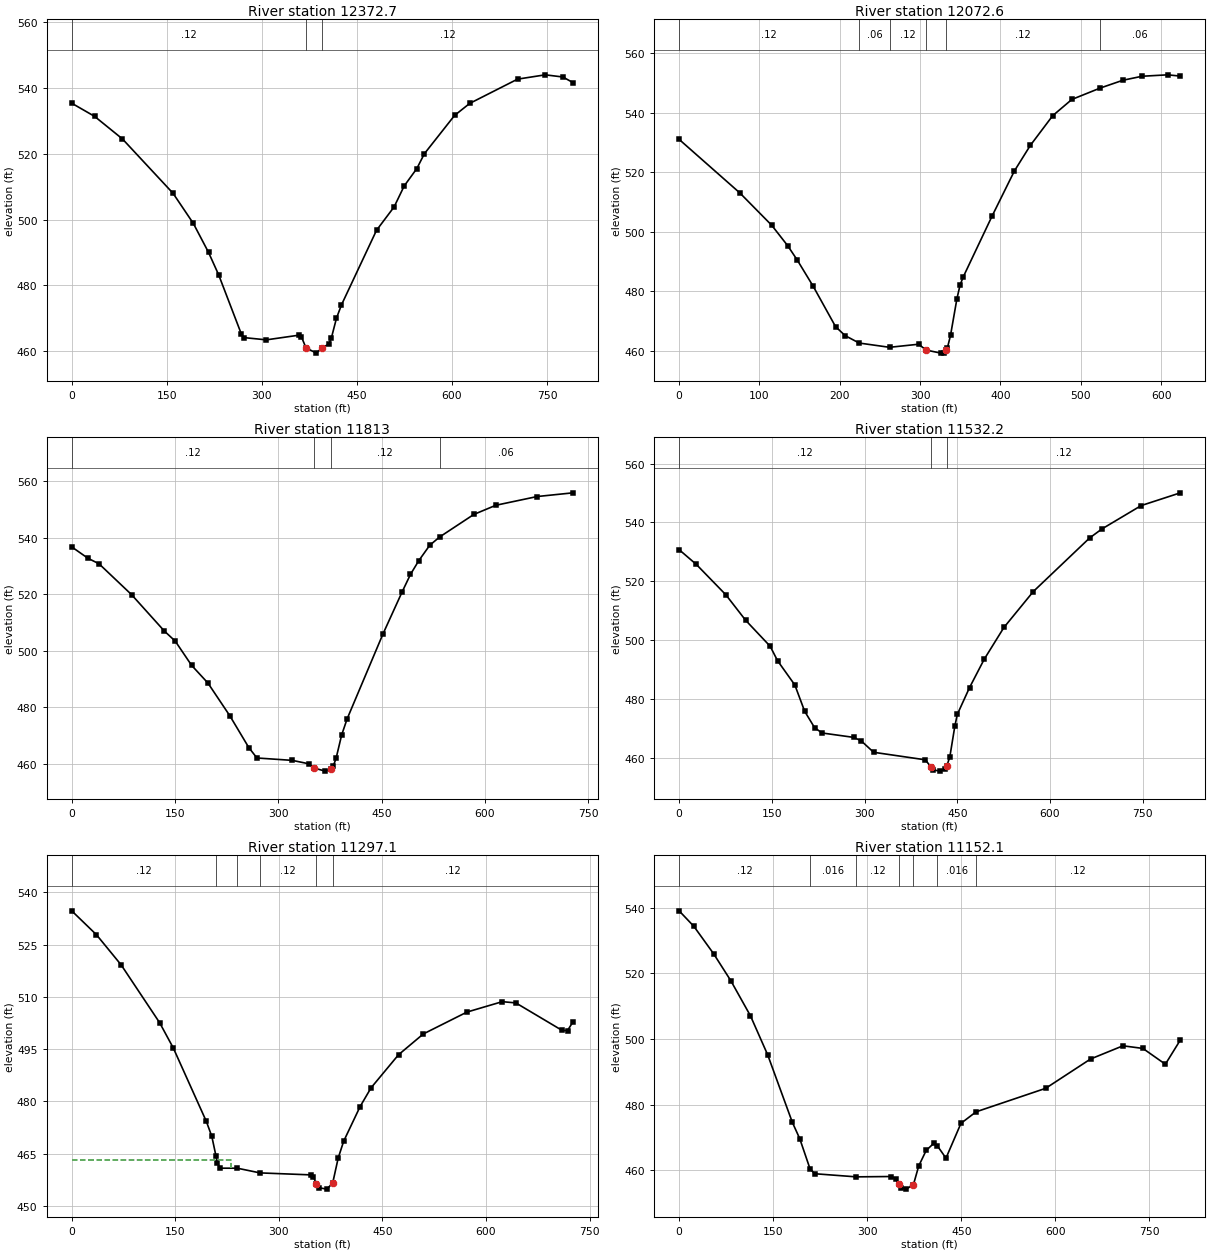
Type RM Length L Ch R = 1 ,12372.7 ,295.1,300,305.2
XS GIS Cut Line= 4
     2392215.921      320936.966     2392057.501      320756.844
     2391922.952      320561.532     2391970.696      320251.202
#Sta/Elev= 30
       0  535.42      36  531.43      80  524.56   159.9  508.01   191.9  498.85
   215.9  490.03   231.9  483.19   267.6  465.23   271.5  464.11   307.1  463.42
   358.5  464.84   362.4  464.37   369.7460.9754   386.1  459.38   394.7460.9175
   405.9  462.18   409.8  464.03   417.8  470.02   425.7  474.07     481  496.76
   508.8  503.89   524.7  510.26   544.6  515.54   556.5  520.05   604.2  531.71
   628.1  535.37   703.6  542.75   747.3  544.06   775.1   543.4     791  541.69
#Mann= 3 ,-1 , 0
       0     .12       0   369.7    .045       0   394.7     .12       0
Bank Sta=369.7,394.7
XS Rating Curve= 0 ,0
Exp/Cntr=0.3,0.1

Type RM Length L Ch R = 1 ,12072.6 ,261.2,259.7,257.8
XS GIS Cut Line= 2
     2392346.238       320778.22     2392098.842      320205.303
#Sta/Elev= 30
       0  531.06    75.5  513.08   115.3  502.18   135.1  495.34   147.1  490.48
   166.9  481.68   194.8  468.09   206.7  465.08  224.17462.5916  261.97461.1559
   298.1  462.19   307.6460.2261   325.9   459.2   329.9  459.35   332.6460.3625
   333.9  460.85   337.9   465.2   345.8  477.41   349.8  482.15   353.8  484.87
   389.5  505.21   417.4  520.44   437.2  529.02   465.1  539.03   488.9  544.48
  524.29548.3198   552.5  550.94   576.4  552.28   608.2  552.76     624  552.33
#Mann= 6 ,-1 , 0
       0     .12       0  224.17     .06       0  261.97     .12       0
   307.6    .045       0   332.6     .12       0  524.29     .06       0
Bank Sta=307.6,332.6
XS Rating Curve= 0 ,0
Exp/Cntr=0.3,0.1

Type RM Length L Ch R = 1 ,11813   ,276.1,280.8,285.5
XS GIS Cut Line= 3
     2392628.435      320707.169     2392458.456      320385.294
     2392288.477       320063.42
#Sta/Elev= 30
       0  536.68    23.7  532.63    39.6  530.71      87  519.76   134.5  506.91
   150.4  503.32   174.1  494.77   197.8  488.51   229.5  476.97   257.2  465.67
     269  461.99   320.5  461.14   344.2  459.94   351.5458.4792     368  457.34
   376.5 458.155     380  459.24     384  461.92     392  470.11     400  475.84
     452  505.85     480  520.83     492  526.95     504  531.79     520  537.26
  534.31540.1826     584  548.16     616  551.41     676   554.5     728  555.81
#Mann= 4 ,-1 , 0
       0     .12       0   351.5    .045       0   376.5     .12       0
  534.31     .06       0
Bank Sta=351.5,376.5
XS Rating Curve= 0 ,0
Exp/Cntr=0.3,0.1

Type RM Length L Ch R = 1 ,11532.2 ,240.2,235,229.6
XS GIS Cut Line= 4
      2392691.29      320678.394     2392761.918      320437.672
     2392702.141      320227.005     2392437.384      320012.161
#Sta/Elev= 30
       0  530.74    27.9  525.71    75.7  515.37   107.5  506.75   147.3  497.88
   159.3  492.95   187.2  484.72   203.1  475.77     219  470.25     231   468.4
   282.7  466.89   294.7  465.69   314.6  461.83   398.2  459.27   408.1456.6703
   410.1  455.86   422.1  455.42     430  456.01   433.1457.2112     438  460.37
     446  470.72     450  474.71   469.8  483.84   493.6   493.5   525.4  504.28
   572.9  516.49   664.1  534.73   683.9  537.78   747.4  545.73   810.8  550.07
#Mann= 3 ,-1 , 0
       0     .12       0   408.1    .045       0   433.1     .12       0
Bank Sta=408.1,433.1
XS Rating Curve= 0 ,0
Exp/Cntr=0.3,0.1

Type RM Length L Ch R = 1 ,11297.1 ,134.7,145,155.3
XS GIS Cut Line= 3
     2393086.038      320520.625     2392849.493      320056.215
     2392693.243      319923.836
#Sta/Elev= 30
       0  534.68    35.8  527.82    71.6  519.16   127.3  502.58   147.2  495.28
     195  474.23   202.9  469.95     209464.2542   210.9  462.34   214.8  460.82
  239.81 460.814  272.66459.4688   346.1   458.9   350.1  458.31   354.1  456.38
   358.1  455.21   369.6  454.81     378  456.57   385.9  463.69   393.9  468.57
   417.7  478.51   433.6   483.9   473.4  493.39   509.2  499.34   572.4  505.62
   623.6  508.61   643.3  508.25   710.2  500.37   718.1  500.32     726  502.81
#Mann= 6 ,-1 , 0
       0     .12       0     209    .016       0  239.81     .06       0
  272.66     .12       0   354.1    .045       0     378     .12       0
#XS Ineff= 2 , 0
          231.17  463.14
Permanent Ineff=
       F       F
Bank Sta=354.1,378
XS Rating Curve= 0 ,0
Exp/Cntr=0.3,0.1

Type RM Length L Ch R = 1 ,11152.1 ,83.4,83,82.6
XS GIS Cut Line= 4
     2393146.802      320477.222     2393059.997      320314.461
     2393051.316      320073.576     2392717.115      319906.475
#Sta/Elev= 30
       0  538.99    23.6  534.25      55  525.93    82.4  517.73   113.8  507.01
   141.3  495.11   180.5  474.62   192.4   469.6  208.68460.4828   216.1  458.96
  282.28458.0058   338.6  458.11   346.5  457.29   350.4   455.9   354.4  454.66
   362.3  454.27   373.7455.6761     382   461.3   393.9  466.04   405.8  468.17
   411.8467.4431   425.5   463.7   449.4   474.3  473.49477.8023   584.5  484.96
     656  493.88   707.7   497.9   739.5   497.1   775.3  492.29   799.2  499.67
#Mann= 7 ,-1 , 0
       0     .12       0  208.68    .016       0  282.28     .12       0
   350.4    .045       0   373.7     .12       0   411.8    .016       0
  473.49     .12       0
Bank Sta=350.4,373.7
XS Rating Curve= 0 ,0
Exp/Cntr=0.3,0.1

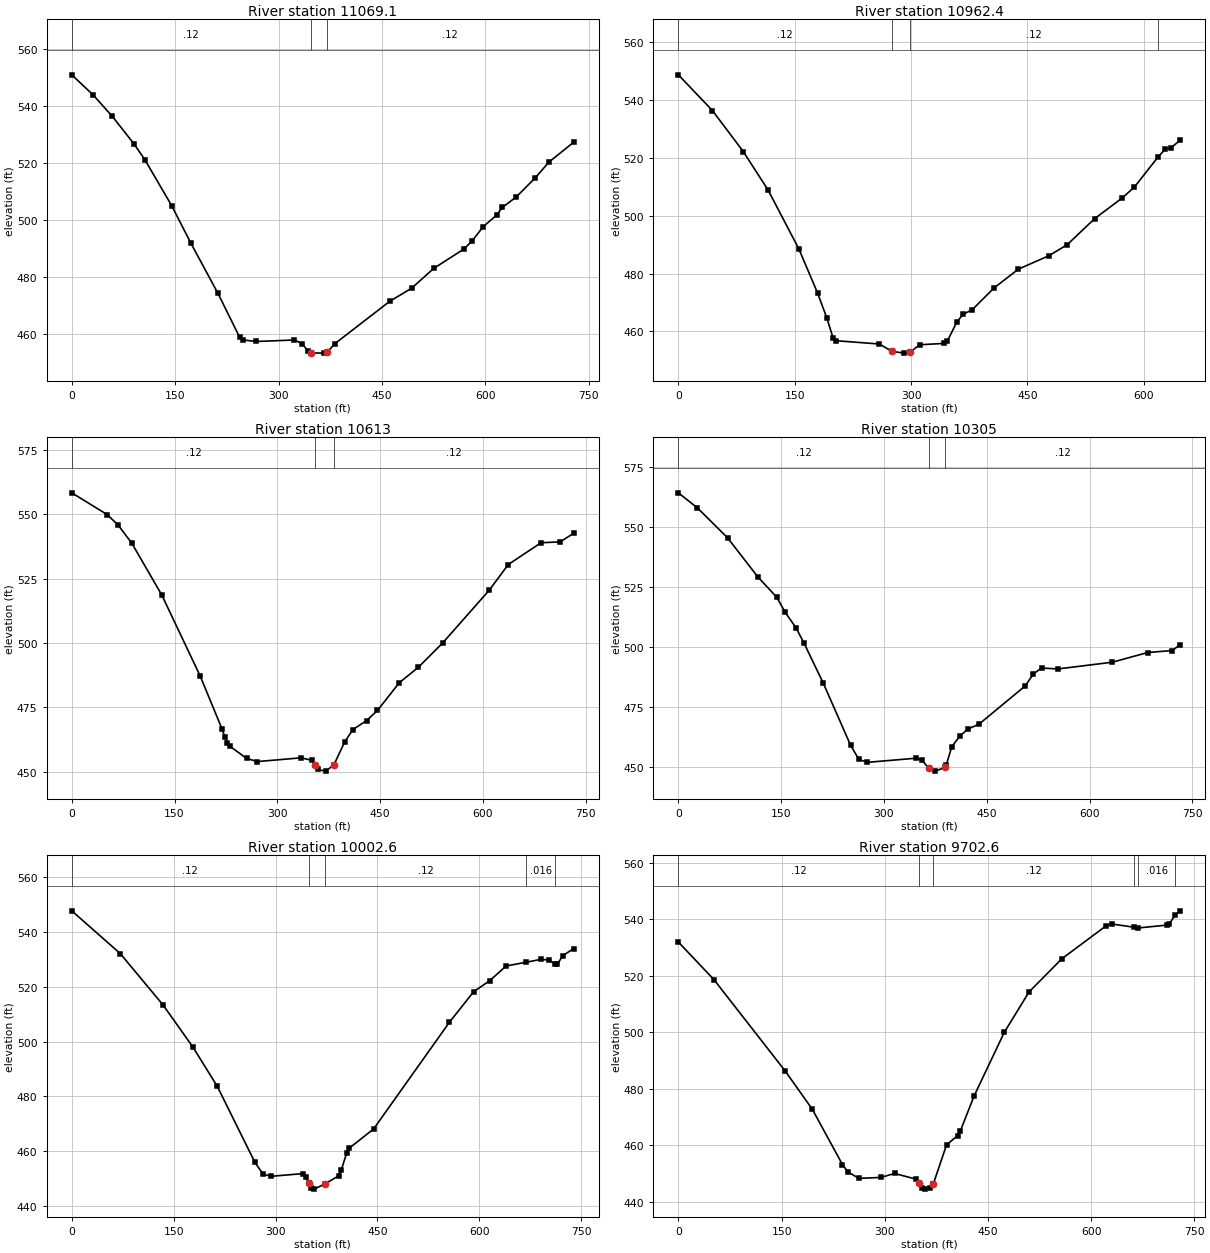
Type RM Length L Ch R = 1 ,11069.1 ,116.2,106.7,97.4
XS GIS Cut Line= 4
     2393227.097      320457.691     2393140.292       320294.93
     2393131.611      320054.045     2393055.656      319761.076
#Sta/Elev= 30
       0  551.02    31.4  543.88    58.9  536.44    90.3  526.81     106  521.29
   145.2  505.05   172.7  492.05   212.1  474.41   243.7  458.96   247.7  458.12
   267.4  457.55   322.8  458.07   334.6  456.77   342.5  454.18   346.5  453.54
   366.2  453.47   370.2  453.73     382  456.84   461.3  471.63   493.2  476.25
   525.1  483.16   568.9  489.96   580.8  492.78   596.7  497.75   616.6   501.9
   624.6  504.55   644.5  508.13   672.4   514.9   692.3  520.44   728.2   527.4
#Mann= 3 ,-1 , 0
       0     .12       0   346.5    .045       0   370.2     .12       0
Bank Sta=346.5,370.2
XS Rating Curve= 0 ,0
Exp/Cntr=0.3,0.1

Type RM Length L Ch R = 1 ,10962.4 ,358,349.4,325.2
XS GIS Cut Line= 3
     2393359.476      320340.503     2393183.695       319978.09
      2393114.25      319743.715
#Sta/Elev= 30
       0  548.64    43.9   536.3    83.8  522.09   115.6  508.88   155.5   488.4
   179.5  473.26   191.4  464.62   199.4  457.85   203.4  456.78   259.2  455.64
   275.2  453.12   291.1  452.49   299.1  452.89   311.1  455.38     343  455.85
     347  456.72   358.9  463.17   366.9  465.89   378.9  467.48   406.7  474.93
   438.3  481.49   477.7  486.14   501.4  489.96   536.8  498.97   572.3   506.1
   588.1  509.89  618.84520.3762   627.5  522.87   635.4  523.52   647.2  526.06
#Mann= 4 ,-1 , 0
       0     .12       0   275.2    .045       0   299.1     .12       0
  618.84     .06       0
Bank Sta=275.2,299.1
XS Rating Curve= 0 ,0
Exp/Cntr=0.3,0.1

Type RM Length L Ch R = 1 ,10613   ,302.3,307.9,308.6
XS GIS Cut Line= 3
     2393713.115      320031.414      2393401.36      319838.449
     2393104.057      319625.076
#Sta/Elev= 30
       0  558.25    51.8   549.8    67.8   545.7    87.7  538.68   131.5  518.55
   187.3  487.26   219.2  466.75   223.2  463.67   227.2  461.28   231.1   459.9
   255.1  455.24     271  454.01   334.8  455.46   350.7  454.48  355.53452.6914
   358.7  450.94   370.6   450.3   382.6  452.73   398.5  461.73   410.4  466.44
   430.3  469.89   446.2  473.85     478  484.58   505.9  490.59   541.7  500.12
   609.3  520.47   637.1  530.44   684.9  538.89   712.7  539.22   732.6  542.56
#Mann= 3 ,-1 , 0
       0     .12       0  355.53    .045       0   382.6     .12       0
Bank Sta=355.53,382.6
XS Rating Curve= 0 ,0
Exp/Cntr=0.3,0.1

Type RM Length L Ch R = 1 ,10305   ,303.4,302.4,294.9
XS GIS Cut Line= 3
     2393859.104      319894.724     2393609.262      319625.692
     2393326.494      319394.312
#Sta/Elev= 30
       0  564.35    27.9  558.03    71.8  545.58   115.7  529.35   143.7  520.73
   155.6   514.6   171.6  508.04   183.6  501.49   211.5  484.89   251.4  458.95
   263.4  453.11   275.4  451.86   347.2   453.6   355.2  452.78   365.3449.5378
   375.1   448.2  388.61449.7263     391  450.76   398.9  458.38   410.8  462.84
   422.8  465.81   438.6  467.77   506.2  483.77   518.1  488.79     530  491.23
   553.8  490.85   633.2  493.65   684.9   497.7   720.6  498.53   732.5  500.99
#Mann= 3 ,-1 , 0
       0     .12       0   365.3    .045       0  388.61     .12       0
Bank Sta=365.3,388.61
XS Rating Curve= 0 ,0
Exp/Cntr=0.3,0.1

Type RM Length L Ch R = 1 ,10002.6 ,296.8,300,299.5
XS GIS Cut Line= 3
     2394076.282      319677.893     2393789.163      319452.987
      2393521.75      319191.459
#Sta/Elev= 30
       0  547.61    71.4  532.04   134.8  513.19   178.4  497.96   214.1  483.73
   269.6     456   281.5  451.75   293.4  450.94   340.9  451.93   344.9  450.86
   348.9  448.44   352.8  446.61   356.8  446.27   372.7  448.19   392.6  451.07
   396.6  453.22   404.5  459.27   408.5   461.2   444.3  468.18   555.7  506.98
   591.5  518.15   615.4  522.22   639.3  527.52  668.44528.8738     691  529.96
     703  529.64  711.59528.1538   714.9  528.22   722.8  531.31   738.8  533.86
#Mann= 5 ,-1 , 0
       0     .12       0   348.9    .045       0   372.7     .12       0
  668.44    .016       0  711.59     .08       0
Bank Sta=348.9,372.7
XS Rating Curve= 0 ,0
Exp/Cntr=0.3,0.1

Type RM Length L Ch R = 1 ,9702.6  ,271.5,273.3,276.2
XS GIS Cut Line= 3
     2394240.106      319493.839     2393985.619      319231.153
     2393720.203      318982.564
#Sta/Elev= 30
       0  531.97    51.7  518.65     155  486.35   194.8  472.65   238.5   453.1
   246.5  450.47   262.4  448.24   294.2  448.56   314.1  449.96   345.9  447.93
   349.8  446.44   353.8  444.75   357.8  444.42   365.7  444.89  370.69446.4134
   389.7  460.11   405.7  463.34   409.7  464.99   429.7  477.42   473.6  499.97
   509.6   514.3   557.6  526.11   621.5   537.7   629.5  538.38  661.67537.2343
  667.83 536.952   709.4  537.96   713.4  538.42  721.82541.5197   729.4  543.03
#Mann= 6 ,-1 , 0
       0     .12       0   349.8    .045       0  370.69     .12       0
  661.67     .08       0  667.83    .016       0  721.82     .06       0
Bank Sta=349.8,370.69
XS Rating Curve= 0 ,0
Exp/Cntr=0.3,0.1

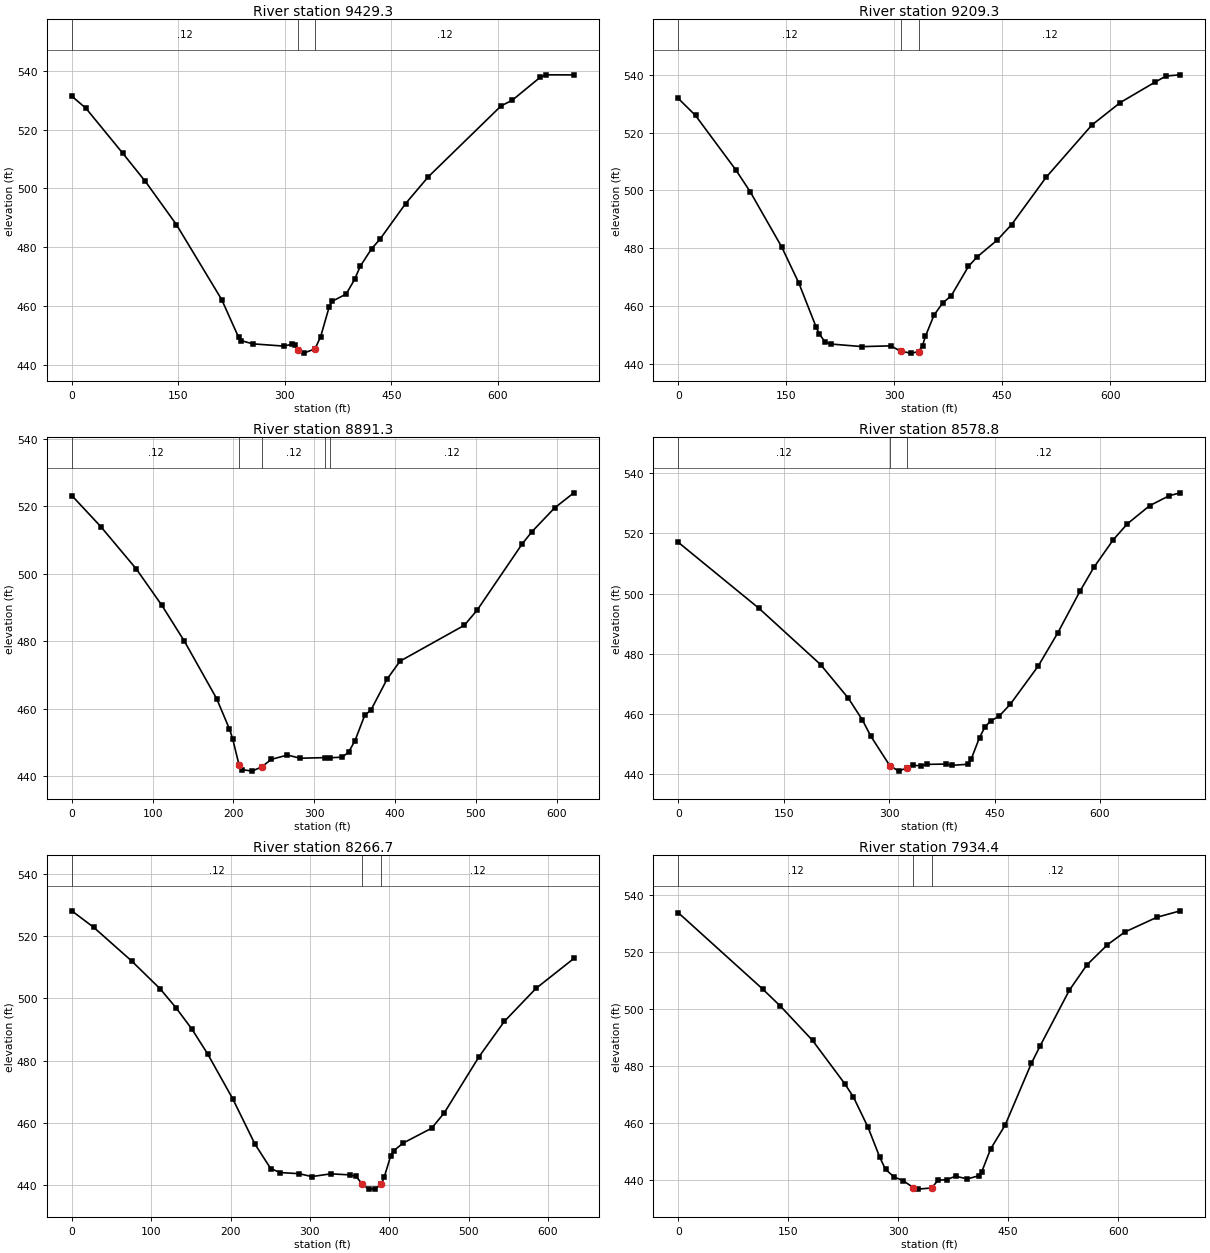
Type RM Length L Ch R = 1 ,9429.3  ,217.3,220,222.4
XS GIS Cut Line= 3
      2394407.87      319315.546     2394073.669      318909.731
     2394038.946      318731.779
#Sta/Elev= 30
       0  531.41    19.9   527.3    71.7     512   103.6  502.38   147.4  487.65
   211.1  462.13     235  449.23     239  448.12   254.9  447.05   298.7  446.28
   310.6  446.96   314.6  446.54   318.6  444.99   326.6  443.89   342.5  445.33
   350.5  449.54   362.4  459.55   366.4  461.52   386.3  463.99   398.3     469
   406.2  473.47   422.2  479.45   434.1  482.72     470  494.79   501.8  503.89
   604.6  528.11   620.3  530.03   659.7  537.86   667.6  538.68     707  538.65
#Mann= 3 ,-1 , 0
       0     .12       0   318.6    .045       0   342.5     .12       0
Bank Sta=318.6,342.5
XS Rating Curve= 0 ,0
Exp/Cntr=0.3,0.1

Type RM Length L Ch R = 1 ,9209.3  ,318.5,318,317.9
XS GIS Cut Line= 3
     2394544.589      319204.869     2394277.662      318792.543
     2394106.221      318677.526
#Sta/Elev= 30
       0  531.82      24  525.91    79.9  507.13    99.8  499.61   143.8  480.43
   167.7  467.88   191.7  452.67   195.7   450.5   203.7  447.67   211.6  446.89
   255.6  445.98   295.5  446.25     309 444.365   323.5  443.73     334444.2165
   339.4  446.36   343.4  449.52   355.4  456.88   367.4  461.05   379.4   463.6
   403.3  473.75   415.3     477   443.3  482.84   463.2  488.18     511  504.49
   574.6  522.58   614.3   530.4   661.9  537.36   677.8  539.56   697.6  539.97
#Mann= 3 ,-1 , 0
       0     .12       0     309    .045       0     334     .12       0
Bank Sta=309,334
XS Rating Curve= 0 ,0
Exp/Cntr=0.3,0.1

Type RM Length L Ch R = 1 ,8891.3  ,314.6,312.5,309.9
XS GIS Cut Line= 2
     2394761.603       319052.96     2394423.061      318532.126
#Sta/Elev= 30
       0  523.21    35.8  514.03    79.6  501.53   111.5  490.67   139.4  480.04
   179.2  463.08   195.1  454.06   199.1  451.13   207.1  443.25     211  442.02
     223  441.58   234.9  442.82   246.9  445.06   266.8  446.34   282.7   445.4
   313.8 445.584  320.07445.5501   334.5  445.71   342.4  447.16   350.4  450.59
   362.4  458.08   370.3  459.73   390.2  468.87   406.2  474.16   485.8  484.79
   501.7  489.31   557.5  508.96   569.4  512.51   597.3  519.52   621.2  524.01
#Mann= 5 ,-1 , 0
       0     .12       0   207.1    .045       0   234.9     .12       0
   313.8     .06       0  320.07     .12       0
Bank Sta=207.1,234.9
XS Rating Curve= 0 ,0
Exp/Cntr=0.3,0.1

Type RM Length L Ch R = 1 ,8578.8  ,308.6,312.1,315.6
XS GIS Cut Line= 3
     2394857.089      318992.196     2394902.662       318738.29
     2394622.714      318378.046
#Sta/Elev= 30
       0  517.04   115.1  495.05   202.4  476.43   242.1  465.19   261.9  458.04
   273.8  452.66   300.8 442.868   313.5     441   325.8 442.119   333.3  442.95
   345.2  442.75   353.2  443.25     381  443.34   388.9  442.91   412.7   443.3
   416.6  444.91   428.6  452.17   436.5  455.77   444.4  457.66   456.3  459.23
   472.2  463.18   511.9  475.86   539.6  486.81   571.4  500.76   591.2   508.7
     619  517.93   638.8  523.17   670.6  529.21   698.3  532.51   714.2  533.48
#Mann= 3 ,-1 , 0
       0     .12       0   300.8    .045       0   325.8     .12       0
Bank Sta=300.8,325.8
XS Rating Curve= 0 ,0
Exp/Cntr=0.3,0.1

Type RM Length L Ch R = 1 ,8266.7  ,330.3,332.3,334.3
XS GIS Cut Line= 2
     2395228.183      318773.012     2394917.853      318221.796
#Sta/Elev= 30
       0  528.21    27.8  522.86    75.6  512.02   111.4  503.08   131.3     497
   151.2  490.19   171.1  482.18   202.9  467.64   230.8   453.1   250.6  445.22
   262.6  443.93   286.4  443.58   302.4  442.64   326.2  443.52   350.1  443.19
   358.1  442.72     366  440.24     374  438.61   381.9   438.6   389.9  440.11
   393.9  442.65   401.8  449.28   405.8  451.01   417.7  453.45   453.5  458.23
   469.4  463.18   513.2  481.26     545  492.59   584.8  503.21   632.6  512.86
#Mann= 3 ,-1 , 0
       0     .12       0     366    .045       0   389.9     .12       0
Bank Sta=366,389.9
XS Rating Curve= 0 ,0
Exp/Cntr=0.3,0.1

Type RM Length L Ch R = 1 ,7934.4  ,331.4,331.5,331.4
XS GIS Cut Line= 2
     2395488.599      318631.953     2395208.651      318006.953
#Sta/Elev= 30
       0  533.67   115.5  506.87   139.4  500.96   183.2  488.96     227  473.87
   238.9  469.19   258.8  458.61   274.7   448.2   282.7  443.86   294.6  441.15
   306.6  439.95   320.5 437.485   326.5  436.94   345.5437.3433   354.4  440.04
   366.3  440.26   378.2  441.46   394.2  440.52   410.1  441.62   414.1  443.09
     426  450.95   445.9  459.36   481.8  481.04   493.7   487.1   533.5  506.56
   557.4   515.4   585.3  522.43   609.2  526.91     653  532.08   684.8  534.32
#Mann= 3 ,-1 , 0
       0     .12       0   320.5    .045       0   345.5     .12       0
Bank Sta=320.5,345.5
XS Rating Curve= 0 ,0
Exp/Cntr=0.3,0.1

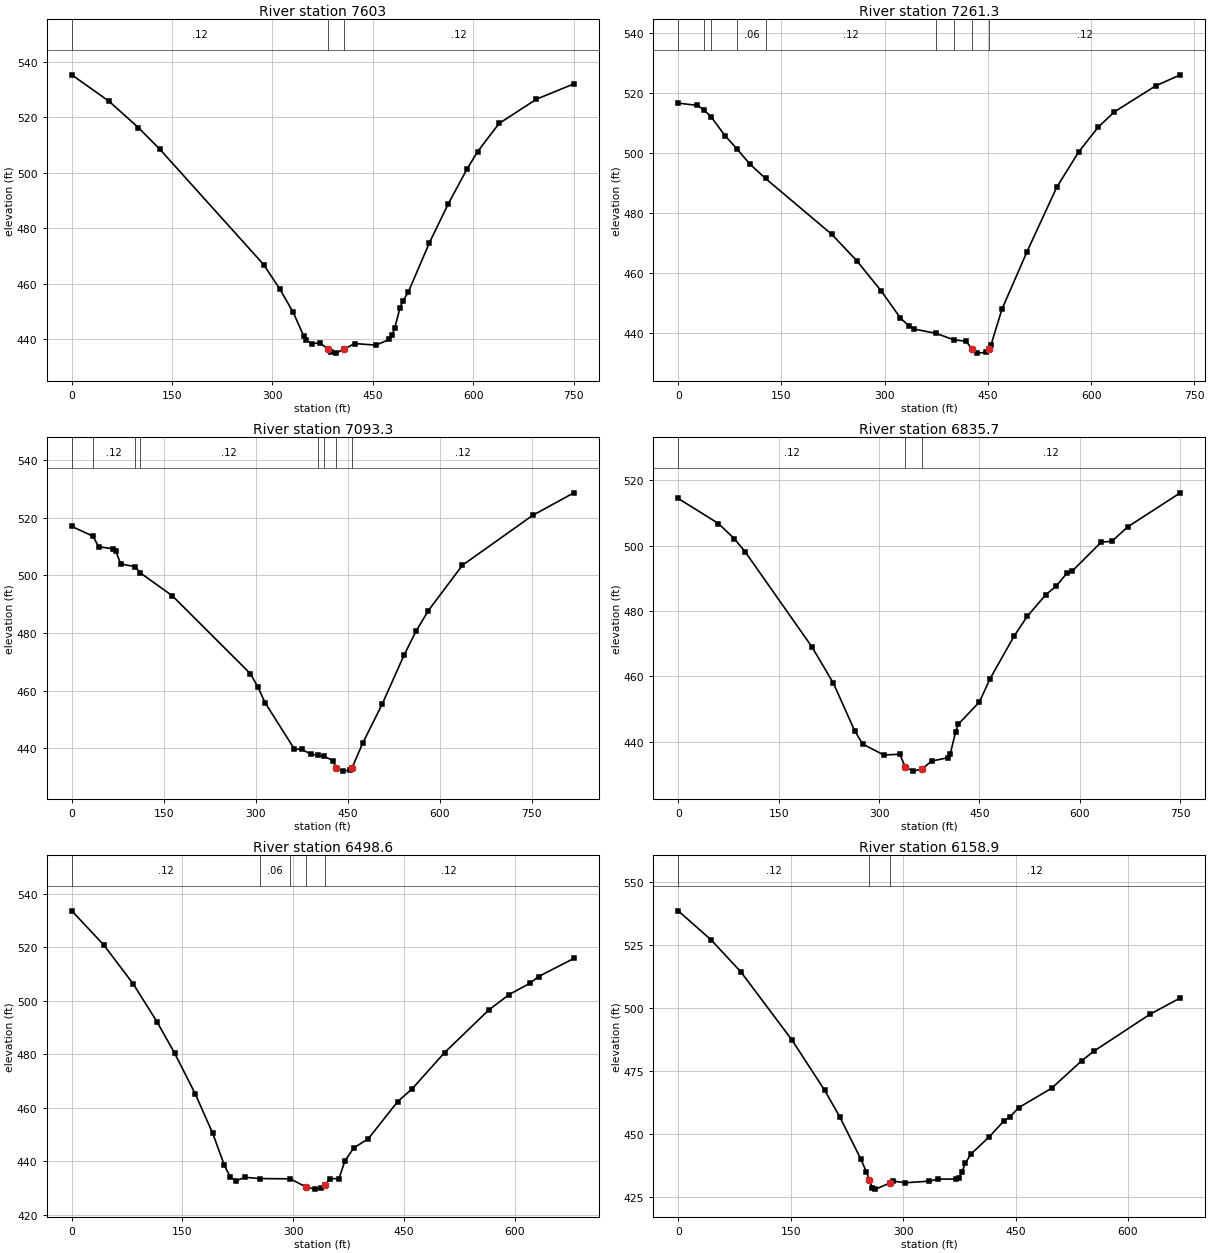
Type RM Length L Ch R = 1 ,7603    ,340.9,341.6,342.4
XS GIS Cut Line= 3
     2395668.721      318566.849     2395668.721      318299.921
     2395464.728      317861.553
#Sta/Elev= 30
       0   535.4    55.8  525.83    99.6  516.33   131.5  508.56   286.9  466.85
   310.9  458.06   330.9  449.66   346.8  441.01   350.8  439.52   358.8  438.32
   370.8  438.62   382.8   436.4   386.8  435.31   394.8  434.91   406.8  436.33
   422.8  438.37   454.7   437.8   474.7  439.87   478.7  441.28   482.7  443.99
   490.7  451.36   494.7  453.63   502.7  456.81   534.6   474.8   562.6  488.75
   590.6  501.33   606.6  507.68   638.6  517.83   694.5   526.6   750.4  532.13
#Mann= 3 ,-1 , 0
       0     .12       0   382.8    .045       0   406.8     .12       0
Bank Sta=382.8,406.8
XS Rating Curve= 0 ,0
Exp/Cntr=0.3,0.1

Type RM Length L Ch R = 1 ,7261.3  ,168.1,168,168
XS GIS Cut Line= 2
     2396035.474      318417.109     2395764.207      317740.026
#Sta/Elev= 30
       0  516.69    27.9  515.93    37.3  514.45   47.92 512.064    67.8  505.86
      86501.2227   103.6  496.44  126.79491.5142   223.2  472.82   259.1  464.09
     295  453.89   322.8  444.87   334.8  442.33   342.8  441.18  374.42439.7635
  399.95437.6335   418.5   437.1   426.5  434.52   434.4  433.15   446.4  433.42
  451.66 434.667   454.4   435.9   470.3  447.83   506.2   466.8     550  488.63
   581.9  500.44   609.8  508.58   633.7   513.8   693.5  522.45   729.4  526.15
#Mann= 9 ,-1 , 0
       0     .08       0    37.3     .12       0   47.92     .08       0
      86     .06       0  126.79     .12       0  374.42     .06       0
  399.95     .12       0   426.5    .045       0  451.66     .12       0
Bank Sta=426.5,451.66
XS Rating Curve= 0 ,0
Exp/Cntr=0.3,0.1

Type RM Length L Ch R = 1 ,7093.3  ,258.7,257.6,256.5
XS GIS Cut Line= 4
     2396091.898      318399.748     2396072.367      318061.206
     2395955.179      317766.067     2395831.481      317661.901
#Sta/Elev= 30
       0     517   34.59513.6027    43.9  509.92    67.8  509.24    71.8   508.4
    79.8  503.95  102.72503.0762  112.03500.8092   163.6  492.98   291.2  465.88
   303.2  461.34   315.2  455.78   362.9  439.71   374.8  439.61   390.7  437.86
  400.94437.6266  411.29437.1758   426.4  435.69   430.4  433.03   441.6  432.06
   454.2  432.42   456.6  433.06   474.1  441.73   505.8  455.23   541.5  472.26
   561.4  480.73   581.2  487.78   636.8  503.53   751.3  520.84   818.4  528.66
#Mann= 8 ,-1 , 0
       0     .08       0   34.59     .12       0  102.72     .08       0
  112.03     .12       0  400.94     .06       0  411.29     .12       0
   430.4    .045       0   456.6     .12       0
Bank Sta=430.4,456.6
XS Rating Curve= 0 ,0
Exp/Cntr=0.3,0.1

Type RM Length L Ch R = 1 ,6835.7  ,338.1,337.1,336
XS GIS Cut Line= 4
     2396502.054      318132.821     2396319.762      317989.592
     2396154.832       317655.39     2396159.172      317509.991
#Sta/Elev= 30
       0  514.37      60  506.72    83.9  502.05    99.9   498.1   199.8     469
   231.8  457.92   263.6  443.39   275.4  439.37   307.2     436     331  436.24
   339.2432.2831   350.8  431.08   364.2431.7538   378.5  434.14   402.3  435.16
   406.3   436.3   414.2  442.96   418.2  445.38   449.9   452.2   465.8   459.3
   501.4  472.21   521.2  478.32     549  484.96   564.9  487.64   580.7  491.58
   588.6  492.21     632  501.05   647.8  501.28   671.4  505.69     750  516.09
#Mann= 3 ,-1 , 0
       0     .12       0   339.2    .045       0   364.2     .12       0
Bank Sta=339.2,364.2
XS Rating Curve= 0 ,0
Exp/Cntr=0.3,0.1

Type RM Length L Ch R = 1 ,6498.6  ,339.8,339.7,337.6
XS GIS Cut Line= 2
     2396708.217      318017.803     2396397.887      317412.335
#Sta/Elev= 30
       0  533.53    43.8  520.65    83.6  506.11   115.4  492.13   139.3  480.42
   167.1  465.31     191  450.44   206.9  438.46   214.8   434.1   222.8  432.73
   234.8  434.02  254.95433.5434  296.18433.4453   317.8430.3463   330.2   429.6
   338.2     430   342.8 431.019   350.1  433.51   362.1  433.49     370  440.02
     382  444.98   401.8   448.4   441.6  462.27   461.5  467.13   505.3  480.61
     565  496.47   592.8  502.28   620.7  506.45   632.6  508.98   680.4  515.74
#Mann= 5 ,-1 , 0
       0     .12       0  254.95     .06       0  296.18     .12       0
   317.8    .045       0   342.8     .12       0
Bank Sta=317.8,342.8
XS Rating Curve= 0 ,0
Exp/Cntr=0.3,0.1

Type RM Length L Ch R = 1 ,6158.9  ,385.4,384.4,384.1
XS GIS Cut Line= 2
     2396970.804      317885.425     2396675.665      317284.296
#Sta/Elev= 30
       0  538.46    43.8  526.95    83.7   514.2   151.5  487.31   195.3  467.31
   215.2   456.9   243.2  440.24   251.1   434.9     255  431.59   259.1  428.63
   263.1  428.11     283   430.6     287  431.29     303  430.63   334.8  431.28
   346.8   432.1   370.7   432.1   374.7  432.63   378.7  435.08   382.7  438.33
   390.6  442.05   414.6  448.78   434.5  455.19   442.5  456.75   454.4  460.47
   498.3  468.17   538.1  478.99   554.1  482.75   629.8  497.54   669.7  503.92
#Mann= 3 ,-1 , 0
       0     .12       0     255    .045       0     283     .12       0
Bank Sta=255,283
XS Rating Curve= 0 ,0
Exp/Cntr=0.3,0.1