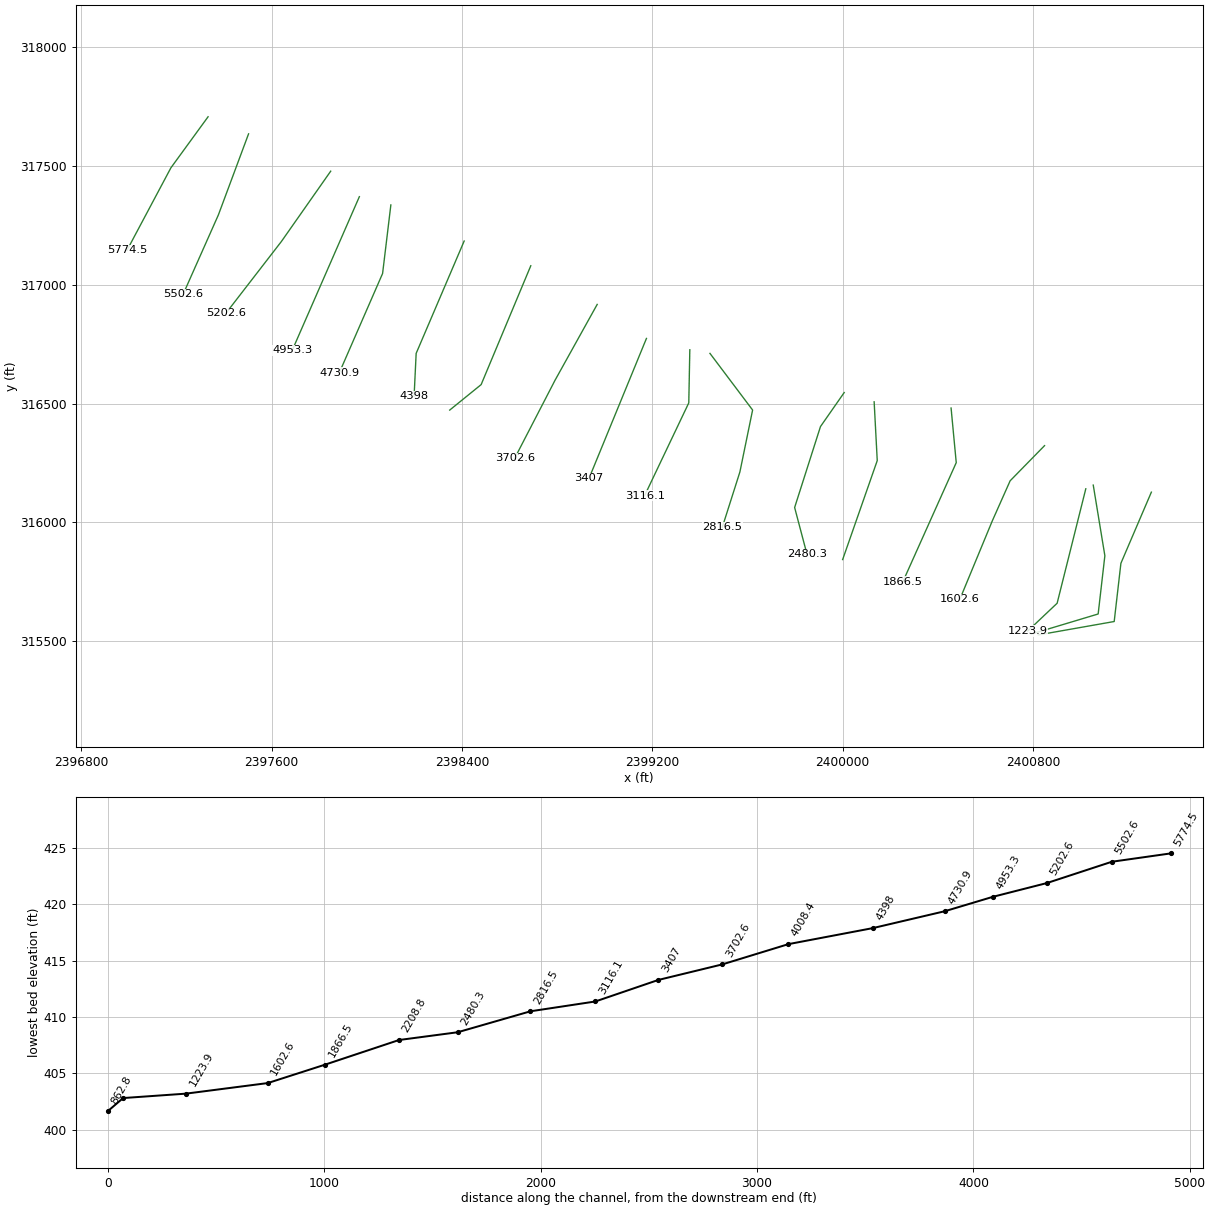
HEC-RAS study MIDDLECRK1.prj: MIDDLECRK1

--- MIDDLECRK1.g01 (geometry) --- (continued)

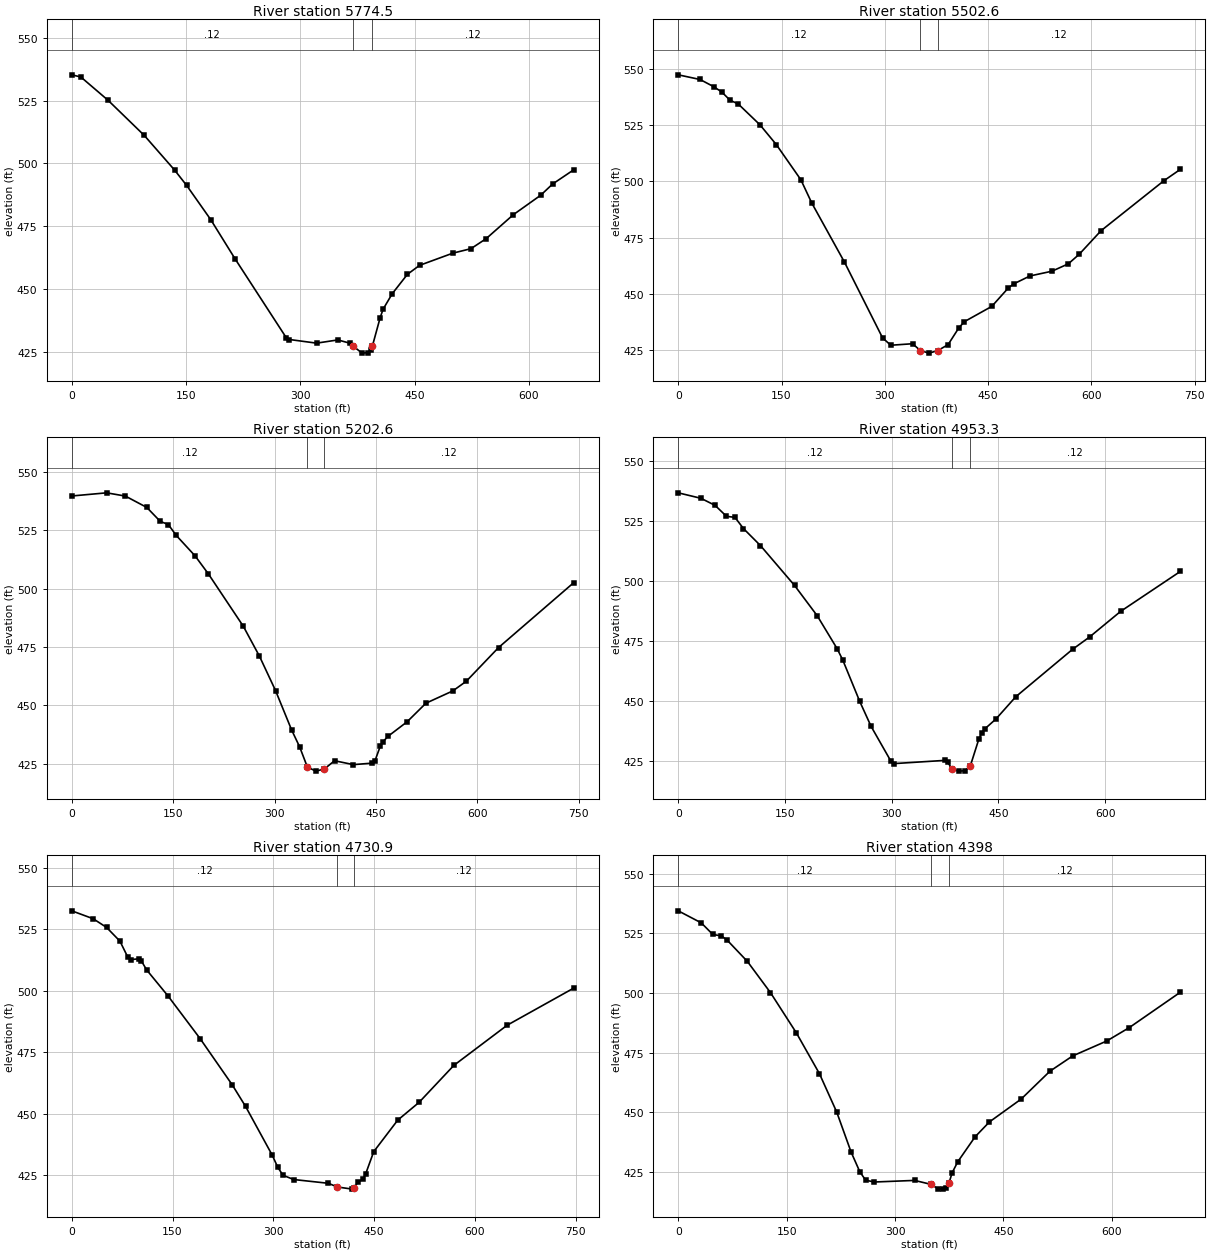
Type RM Length L Ch R = 1 ,5774.5  ,268.9,271.9,273.5
XS GIS Cut Line= 3
     2397333.217      317707.474     2397176.967       317492.63
     2396992.505      317145.408
#Sta/Elev= 30
       0  535.22    11.9  534.36    47.6   525.1    95.2  511.09   134.8  497.37
   150.7  491.24   182.4  477.59   214.1   462.1   281.5  430.62   285.5  429.93
   321.2  428.48   349.1  429.76   364.9  428.47   368.9   427.4   380.8  424.51
   388.8  424.72   392.7  425.66  394.39427.2359   404.7  438.68   408.6  442.03
   420.5  448.15   440.4  455.85   456.3  459.42     500  464.28   523.8  466.06
   543.7  470.04   579.4  479.58   615.2   487.3     631   491.8   658.8  497.47
#Mann= 3 ,-1 , 0
       0     .12       0   368.9    .045       0  394.39     .12       0
Bank Sta=368.9,394.39
XS Rating Curve= 0 ,0
Exp/Cntr=0.3,0.1

Type RM Length L Ch R = 1 ,5502.6  ,306,300,294.3
XS GIS Cut Line= 3
     2397503.431      317635.649     2397376.557      317294.391
       2397228.5      316960.603
#Sta/Elev= 30
       0  547.31    31.7  545.24    51.4  542.07    63.3  539.67    75.2  536.05
    87.1  534.38   118.7  525.12   142.5  516.32   178.1  500.73   193.9  490.43
   241.4  464.18   296.8  430.53   308.7  427.27   340.3  427.94   351.6424.9365
   364.1  423.77   376.6 424.846   391.9  427.53   407.7  435.06   415.7  437.76
   455.4  444.52   479.2  452.62   487.1  454.49   510.9  458.03   542.7  460.13
   566.5   463.4   582.4  467.66   614.1  478.12   705.4  500.31   729.2  505.33
#Mann= 3 ,-1 , 0
       0     .12       0   351.6    .045       0   376.6     .12       0
Bank Sta=351.6,376.6
XS Rating Curve= 0 ,0
Exp/Cntr=0.3,0.1

Type RM Length L Ch R = 1 ,5202.6  ,244.8,249.3,254.9
XS GIS Cut Line= 3
     2397848.625       317478.49      2397641.69      317182.869
     2397408.403      316880.577
#Sta/Elev= 30
       0  539.59    51.6  540.94    79.3  539.55     111  534.69   130.9  528.72
   142.8  527.38   154.6   522.7   182.4  513.97   202.2  506.21   253.8  483.83
   277.6  471.07   301.4  456.36   325.2   439.5   337.1  432.25   348.4423.6935
   360.8  421.88   373.4422.7355   388.7  426.33   416.5  424.66   444.4   425.3
   448.4   426.2   456.3   432.5   460.3  434.45   468.2  436.86   496.1     443
   523.9  450.94   563.7   456.2   583.6  460.33   631.3  474.74   742.7  502.55
#Mann= 3 ,-1 , 0
       0     .12       0   348.4    .045       0   373.4     .12       0
Bank Sta=348.4,373.4
XS Rating Curve= 0 ,0
Exp/Cntr=0.3,0.1

Type RM Length L Ch R = 1 ,4953.3  ,222.7,222.4,222.2
XS GIS Cut Line= 2
     2397969.068      317371.102      2397686.95      316724.401
#Sta/Elev= 30
       0  536.65    31.9  534.37    51.8  531.42    67.8  526.86    79.7  526.42
    91.7  521.75   115.6  514.65   163.4  498.07   195.3  485.43   223.2  471.74
   231.2  466.99   255.1   449.7   271.1  439.27     299  424.74     303  423.79
   374.7  425.14   378.7  424.36   385.3 421.356   394.6  420.66   402.6  420.82
   410.3422.6535   422.5  434.06   426.5  436.44   430.5  438.17   446.5  442.39
   474.4  451.67   554.1  471.41     578  476.55   621.8  487.26   705.6  503.88
#Mann= 3 ,-1 , 0
       0     .12       0   385.3    .045       0   410.3     .12       0
Bank Sta=385.3,410.3
XS Rating Curve= 0 ,0
Exp/Cntr=0.3,0.1

Type RM Length L Ch R = 1 ,4730.9  ,332.8,332.9,332.5
XS GIS Cut Line= 3
     2398101.446       317336.38     2398066.724      317047.751
     2397884.433      316628.915
#Sta/Elev= 30
       0  532.45    31.9  529.23    51.8  525.71    71.7  520.13    83.6  513.53
    87.6  512.61    99.6  512.97   103.5  512.15   111.5  508.44   143.4  497.83
   191.2  480.49   238.9  461.75   258.8  452.96   298.6   433.1   306.6   428.3
   314.5  425.01   330.4  423.28   382.1  421.75   395.2 420.259   417.8  419.38
   420.2 419.836   425.8  422.18   433.7  423.44   437.7  425.69   449.6  434.62
   485.3  447.41   517.1  454.64   568.8  469.64   648.2  485.97   747.5  501.08
#Mann= 3 ,-1 , 0
       0     .12       0   395.2    .045       0   420.2     .12       0
Bank Sta=395.2,420.2
XS Rating Curve= 0 ,0
Exp/Cntr=0.3,0.1

Type RM Length L Ch R = 1 ,4398    ,387.8,389.6,389.8
XS GIS Cut Line= 3
     2398409.606       317184.47     2398207.783       316711.38
     2398199.103      316531.258
#Sta/Elev= 30
       0  534.47    31.9  529.42    47.8  524.57    59.8  523.96    67.8  522.15
    95.7  513.26   127.6  500.21   163.5  483.31   195.4  466.23   219.3  450.16
   239.2  433.39   251.2  425.19   259.2  421.65   271.1  420.86     327  421.53
   349.9419.8675   358.8  418.12   366.8  417.88   370.8  418.39   374.9420.6323
   378.8  424.62   386.8  429.36   410.7  439.78   430.6  446.04   474.5  455.61
   514.3  467.28   545.7  473.67   592.8  479.92   624.1  485.55   694.7  500.36
#Mann= 3 ,-1 , 0
       0     .12       0   349.9    .045       0   374.9     .12       0
Bank Sta=349.9,374.9
XS Rating Curve= 0 ,0
Exp/Cntr=0.3,0.1

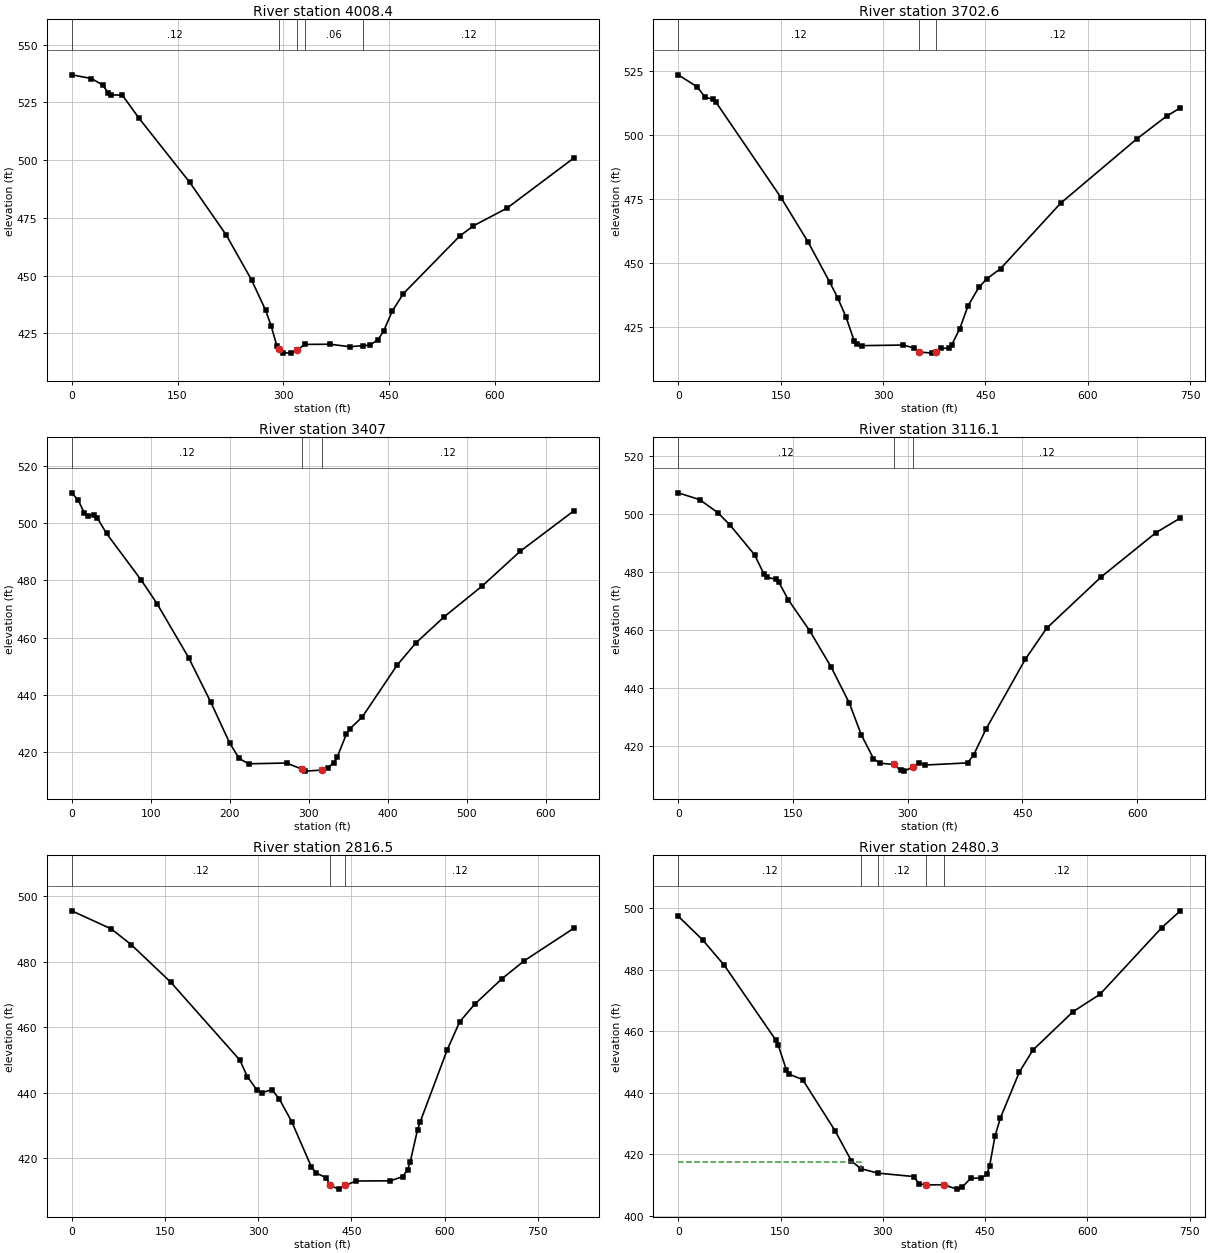
Type RM Length L Ch R = 1 ,4008.4  ,308.2,305.8,303.6
XS GIS Cut Line= 3
     2398689.554      317080.303     2398480.887      316579.907
     2398348.842      316472.665
#Sta/Elev= 30
       0  536.98    27.9  535.38    43.8  532.58    51.8  529.13    55.8  528.34
    71.8  528.14    95.7  518.07   167.4  490.39   219.3  467.54   255.1  448.12
   275.1  434.98     283  428.07     291  419.55  293.49418.0809     299  416.66
     311  416.46   318.9  417.69  330.85420.2361   366.8  420.31   394.7  419.21
  413.42419.7259   422.6  419.88   434.5  422.28   442.5  426.06   454.5  434.54
   470.4   442.2   550.1  467.08   569.8  471.58   617.3  479.21   712.3  500.96
#Mann= 5 ,-1 , 0
       0     .12       0  293.49    .045       0   318.9     .12       0
  330.85     .06       0  413.42     .12       0
Bank Sta=293.49,318.9
XS Rating Curve= 0 ,0
Exp/Cntr=0.3,0.1

Type RM Length L Ch R = 1 ,3702.6  ,293.5,295.6,297.8
XS GIS Cut Line= 3
     2398968.706      316917.569     2398791.784      316598.821
     2398621.675      316269.279
#Sta/Elev= 30
       0  523.37    27.7  518.68    39.6  514.56    51.5  513.84    55.5  512.59
   150.6  475.38   190.2  458.06   221.9  442.39   233.8   436.1   245.7  428.82
   257.6  419.51   261.5  418.28   269.4  417.59   328.9  417.81   344.7  416.76
   352.1 415.121   372.1  414.66   377.1 415.138   384.5   416.5   396.5  416.64
   400.4  417.78   412.4  424.24   424.4  433.09   440.3  440.36   452.3  443.76
   472.2  447.68     560   473.2   671.6  498.32   715.5  507.27   735.4  510.46
#Mann= 3 ,-1 , 0
       0     .12       0   352.1    .045       0   377.1     .12       0
Bank Sta=352.1,377.1
XS Rating Curve= 0 ,0
Exp/Cntr=0.3,0.1

Type RM Length L Ch R = 1 ,3407    ,291.7,290.9,289.4
XS GIS Cut Line= 2
     2399175.665      316774.314      2398934.78      316186.206
#Sta/Elev= 30
       0  510.66       8  508.13      16   503.6      20   502.6      28  502.88
      32     502      44  496.44    87.9  480.12   107.9  471.89   147.9  452.99
   175.9  437.44   199.8  423.16   211.8  417.72   223.8  415.84   271.8  416.12
     292 413.907   295.8  413.28     317 413.667   323.8  414.35   331.8  416.29
   335.8  418.06   347.7  426.31   351.7  428.02   367.7  432.22   411.7  450.32
   435.7  458.18   471.6  467.34   519.6  478.08   567.6   490.2   635.5  504.35
#Mann= 3 ,-1 , 0
       0     .12       0     292    .045       0     317     .12       0
Bank Sta=292,317
XS Rating Curve= 0 ,0
Exp/Cntr=0.3,0.1

Type RM Length L Ch R = 1 ,3116.1  ,294.5,299.6,304.6
XS GIS Cut Line= 3
     2399357.957      316726.571     2399353.617      316503.046
     2399167.777      316112.076
#Sta/Elev= 30
       0  507.31      28  504.96    51.9  500.45    67.9  496.14    99.8  485.95
   111.8  479.46   115.8  478.23   127.8   477.5   131.7  476.44   143.7  470.52
   171.7  459.84   199.6  447.41   223.6   434.9   239.4  423.86   255.3  415.71
   263.3  414.13   281.9413.6677   291.1  411.59     295  411.37   306.9412.7378
   314.9  414.25   322.8  413.47   378.4  414.21   386.4  417.01   402.3   425.8
   453.9  449.96   481.7  460.62   553.2  478.36   624.7  493.58   656.5  498.62
#Mann= 3 ,-1 , 0
       0     .12       0   281.9    .045       0   306.9     .12       0
Bank Sta=281.9,306.9
XS Rating Curve= 0 ,0
Exp/Cntr=0.3,0.1

Type RM Length L Ch R = 1 ,2816.5  ,340.7,336.2,328.7
XS GIS Cut Line= 4
     2399442.592       316711.38     2399621.841      316472.843
      2399568.46      316212.248     2399494.676      315980.043
#Sta/Elev= 30
       0  495.49    63.6  489.96    95.5  485.19   159.1  473.73   270.5   449.9
   282.5  444.87   298.4  440.65   306.3  439.99   322.2  440.86   334.1  437.99
     354  431.08   385.7  417.24   393.7   415.4   409.6  413.94   415.4411.6865
   429.4   410.5   440.4411.6243   457.2  412.98   512.8  413.04   532.6  414.32
   540.6  416.49   544.5   418.7   556.4   428.6   560.4  430.89   604.3  453.08
   624.3  461.61   648.3  466.94   692.2  474.73   728.2  480.24     808  490.18
#Mann= 3 ,-1 , 0
       0     .12       0   415.4    .045       0   440.4     .12       0
Bank Sta=415.4,440.4
XS Rating Curve= 0 ,0
Exp/Cntr=0.3,0.1

Type RM Length L Ch R = 1 ,2480.3  ,272.1,271.4,270.7
XS GIS Cut Line= 4
     2400006.828      316546.449     2399907.088      316403.193
     2399798.495      316062.508     2399850.578      315865.026
#Sta/Elev= 30
       0  497.35    35.7  489.69    67.4  481.44   142.8  457.21   146.8  455.34
   158.7  447.33   162.7  445.99   182.5  444.24   230.2  427.55     254   417.8
  267.66   415.3  292.84413.8424   345.4  412.73   353.3  410.36   364.1 410.009
   389.1  410.07     409  408.64   416.9  409.38   428.8  412.12   444.7  412.27
   452.7  413.47   456.6  416.05   464.6  425.88   472.5  431.76   500.4  446.73
   520.2  453.85   579.3  466.37   618.5  471.95   708.9  493.58   736.4  499.11
#Mann= 5 ,-1 , 0
       0     .12       0  267.66     .06       0  292.84     .12       0
   364.1    .045       0   389.1     .12       0
#XS Ineff= 2 , 0
          267.49   417.4
Permanent Ineff=
       F       F
Bank Sta=364.1,389.1
XS Rating Curve= 0 ,0
Exp/Cntr=0.3,0.1

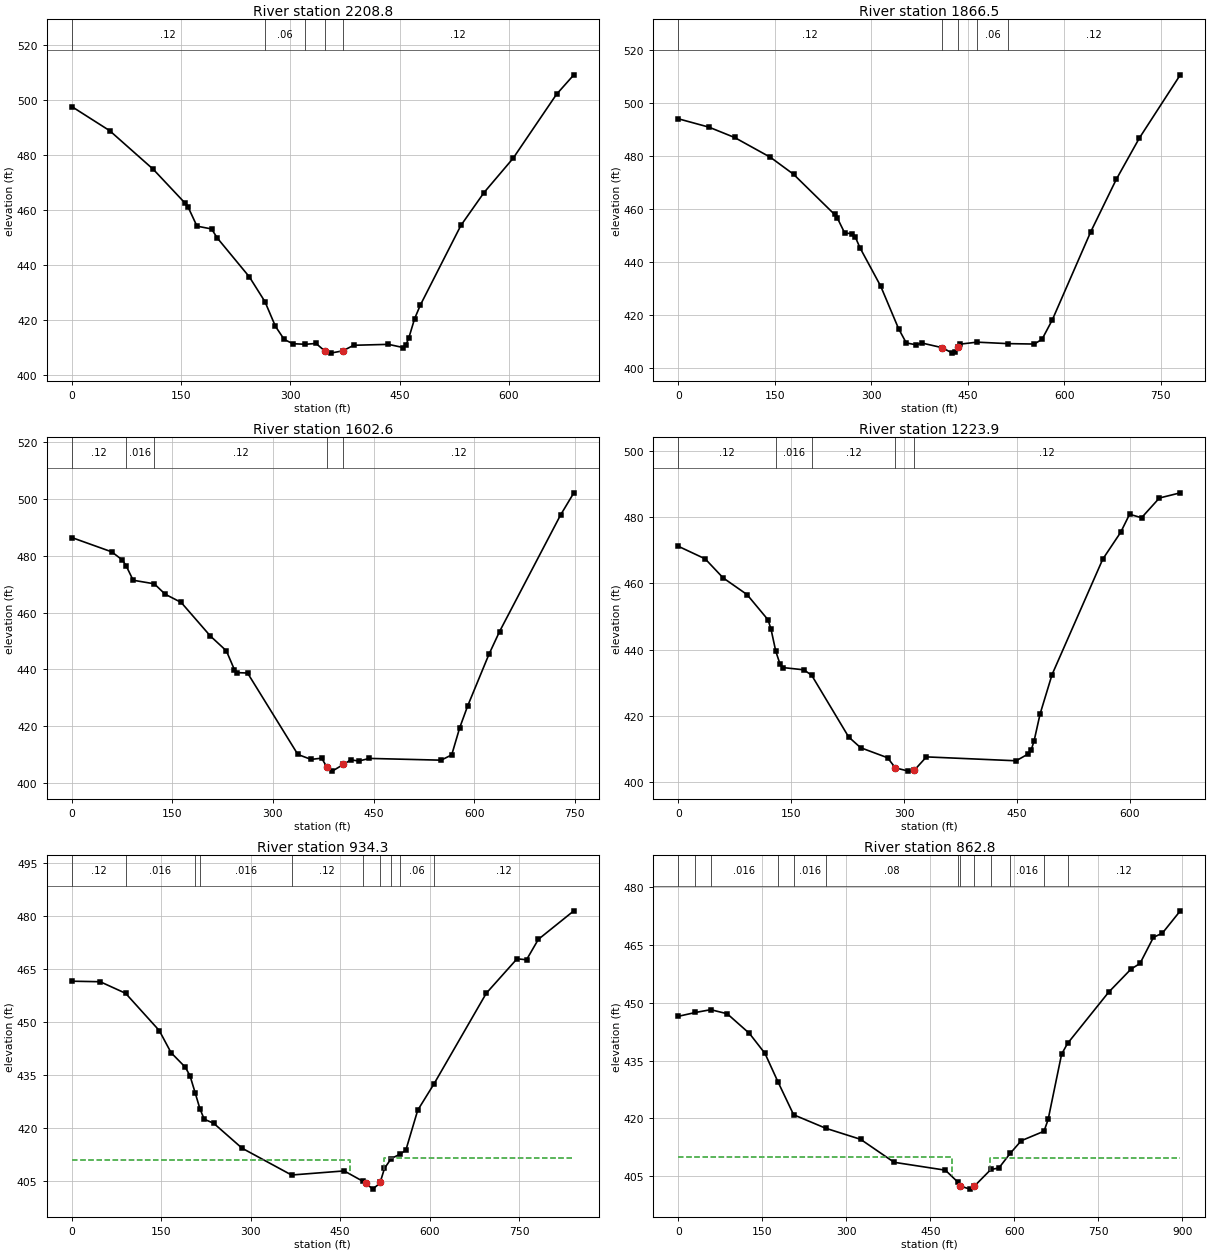
Type RM Length L Ch R = 1 ,2208.8  ,344.2,342.3,340.3
XS GIS Cut Line= 3
     2400132.696      316507.387     2400145.717      316259.991
     2400000.318      315843.324
#Sta/Elev= 30
       0  497.52      52  488.76   111.9  474.71   155.8  462.35   159.8  460.93
   171.8  454.08   191.8  453.06   199.8  449.73   243.7  435.65  265.09426.6493
   279.5  417.68   291.5  412.93   303.4  411.37  320.58411.1648   335.2  411.46
   347.1  408.77   355.1  407.95   371.8  408.77   386.9   410.8   434.6  411.14
   454.5  409.99   458.4  410.84   462.4  413.36   470.4   420.4   478.3  425.38
     534  454.34   565.8   466.3   605.6  478.71   665.2  501.97     689  509.05
#Mann= 5 ,-1 , 0
       0     .12       0  265.09     .06       0  320.58     .12       0
   347.1    .045       0   371.8     .12       0
Bank Sta=347.1,371.8
XS Rating Curve= 0 ,0
Exp/Cntr=0.3,0.1

Type RM Length L Ch R = 1 ,1866.5  ,262.2,263.9,266.1
XS GIS Cut Line= 3
     2400456.047      316481.345     2400477.748       316251.31
     2400253.262      315749.713
#Sta/Elev= 30
       0  494.03    47.8  490.87    87.6  486.98   143.4  479.51   179.3  473.12
     243     458     247  456.82   258.9  450.95   270.9  450.79   274.9  449.68
   282.8  445.33   314.7  431.02   342.6  414.96   354.5  409.61   370.4  408.86
   378.4  409.59   410.2  407.82   426.2  405.76   430.2  406.27   434.2     408
   438.1  409.14  464.49409.8947  512.24409.3403   553.6  409.18   565.6  410.98
   581.5  418.24   641.2  451.39     681  471.18   716.9  486.75   780.6  510.58
#Mann= 5 ,-1 , 0
       0     .12       0   410.2    .045       0   434.2     .12       0
  464.49     .06       0  512.24     .12       0
Bank Sta=410.2,434.2
XS Rating Curve= 0 ,0
Exp/Cntr=0.3,0.1

Type RM Length L Ch R = 1 ,1602.6  ,374.1,378.7,382.7
XS GIS Cut Line= 4
     2400848.842      316322.925     2400704.296      316174.976
     2400628.953       316005.45     2400492.939      315676.224
#Sta/Elev= 30
       0  486.44    59.7  481.39    75.6  478.49    81.1  476.47    91.5   471.4
  123.05470.1331   139.2  466.48   163.1  463.58   206.8   451.7   230.5  446.52
   242.4  439.94   246.3  438.84   262.1   438.7   337.1     410   356.8  408.26
   372.6   408.7   379.9405.7377   388.4  404.13   404.9 406.475   416.1   408.1
     428  407.69   443.8  408.61   550.7  407.99   566.5  409.86   578.4  419.41
   590.2  427.05   621.9  445.23   637.8  453.31   728.8  494.39   748.6   502.2
#Mann= 5 ,-1 , 0
       0     .12       0    81.1    .016       0  123.05     .12       0
   379.9    .045       0   404.9     .12       0
Bank Sta=379.9,404.9
XS Rating Curve= 0 ,0
Exp/Cntr=0.3,0.1

Type RM Length L Ch R = 1 ,1223.9  ,285.7,289.6,293.5
XS GIS Cut Line= 3
     2401022.236      316141.284     2400901.794      315659.514
     2400778.096      315542.326
#Sta/Elev= 30
       0  471.27    35.8  467.45    59.6   461.7    91.4  456.64   119.2  449.02
   123.2  446.22  129.58439.4806   135.1  435.66     139  434.54   166.9  433.86
  177.29432.2039   226.4  413.53   242.3  410.28   278.1  407.24   288.4 404.182
   305.9  403.19   313.4403.4084   329.7   407.5   448.9  406.32   464.8  408.37
   468.8  409.51   472.8  412.41   480.7  420.48   496.6  432.41     564  467.37
   587.7  475.46   599.6  480.95   615.5   479.9   639.2  485.87     667  487.44
#Mann= 5 ,-1 , 0
       0     .12       0  129.58    .016       0  177.29     .12       0
   288.4    .045       0   313.4     .12       0
Bank Sta=288.4,313.4
XS Rating Curve= 0 ,0
Exp/Cntr=0.3,0.1

Type RM Length L Ch R = 1 ,934.3   ,71.2,71.5,71.8
XS GIS Cut Line= 4
     2401053.573      316156.779     2401102.401       315859.47
     2401074.189      315614.244     2400793.156      315529.609
#Sta/Elev= 30
       0   461.6    47.6  461.45   90.22 458.178   146.7  447.63   166.5  441.37
   190.3  437.28   198.2  434.85  206.88430.0155  214.73 425.564     222  422.57
   237.9  421.42   285.4  414.38  368.43406.7914   456.6  407.95   488.4  404.98
   492.4   404.6   504.3   402.8   516.3  404.44   517.4  404.94   524.2  408.68
  535.53 411.461  549.74412.6361     560  413.82   579.9  425.12  607.48432.6471
   694.9  458.21   746.4  467.94   762.3  467.66   782.1  473.44   841.6   481.5
#Mann= 10 ,-1 , 0
       0     .12       0   90.22    .016       0  206.88     .12       0
  214.73    .016       0  368.43     .12       0   488.4    .045       0
   516.3     .12       0  535.53     .08       0  549.74     .06       0
  607.48     .12       0
#XS Ineff= 2 , 0
          466.46  410.98  523.22          411.49
Permanent Ineff=
       F       F
Bank Sta=492.4,517.4
XS Rating Curve= 0 ,0
Exp/Cntr=0.3,0.1

Type RM Length L Ch R = 1 ,862.8   ,171.9,167.5,162.4
XS GIS Cut Line= 4
     2401297.844      316127.178     2401169.806      315827.699
     2401141.594      315582.474     2400822.584       315526.05
#Sta/Elev= 30
       0  446.51   30.59447.5037   58.07448.2356    87.4  447.18   127.1  442.07
   154.9  436.87  177.92 429.542  206.04420.9437   263.5417.4333   325.7  414.56
   385.4   408.6     477  406.55  498.86403.5104  503.03402.4582   520.8  401.63
   528.8  402.41  558.17406.7281   572.5  407.11  592.99410.9615   612.5   414.2
  653.12416.6689   660.5  419.72   684.5  436.67  695.12439.4605   768.5  452.77
   808.5  458.78   824.5  460.23   848.5  467.02   864.5  468.12   896.5  473.91
#Mann= 13 ,-1 , 0
       0    .016       0   30.59     .12       0   58.07    .016       0
  177.92     .08       0  206.04    .016       0   263.5     .08       0
  498.86     .12       0  503.03    .045       0   528.8     .12       0
  558.17     .06       0  592.99    .016       0  653.12     .06       0
  695.12     .12       0
#XS Ineff= 2 , 0
          488.13  409.86  556.24          409.59
Permanent Ineff=
       F       F
Bank Sta=503.03,528.8
XS Rating Curve= 0 ,0
Exp/Cntr=0.3,0.1