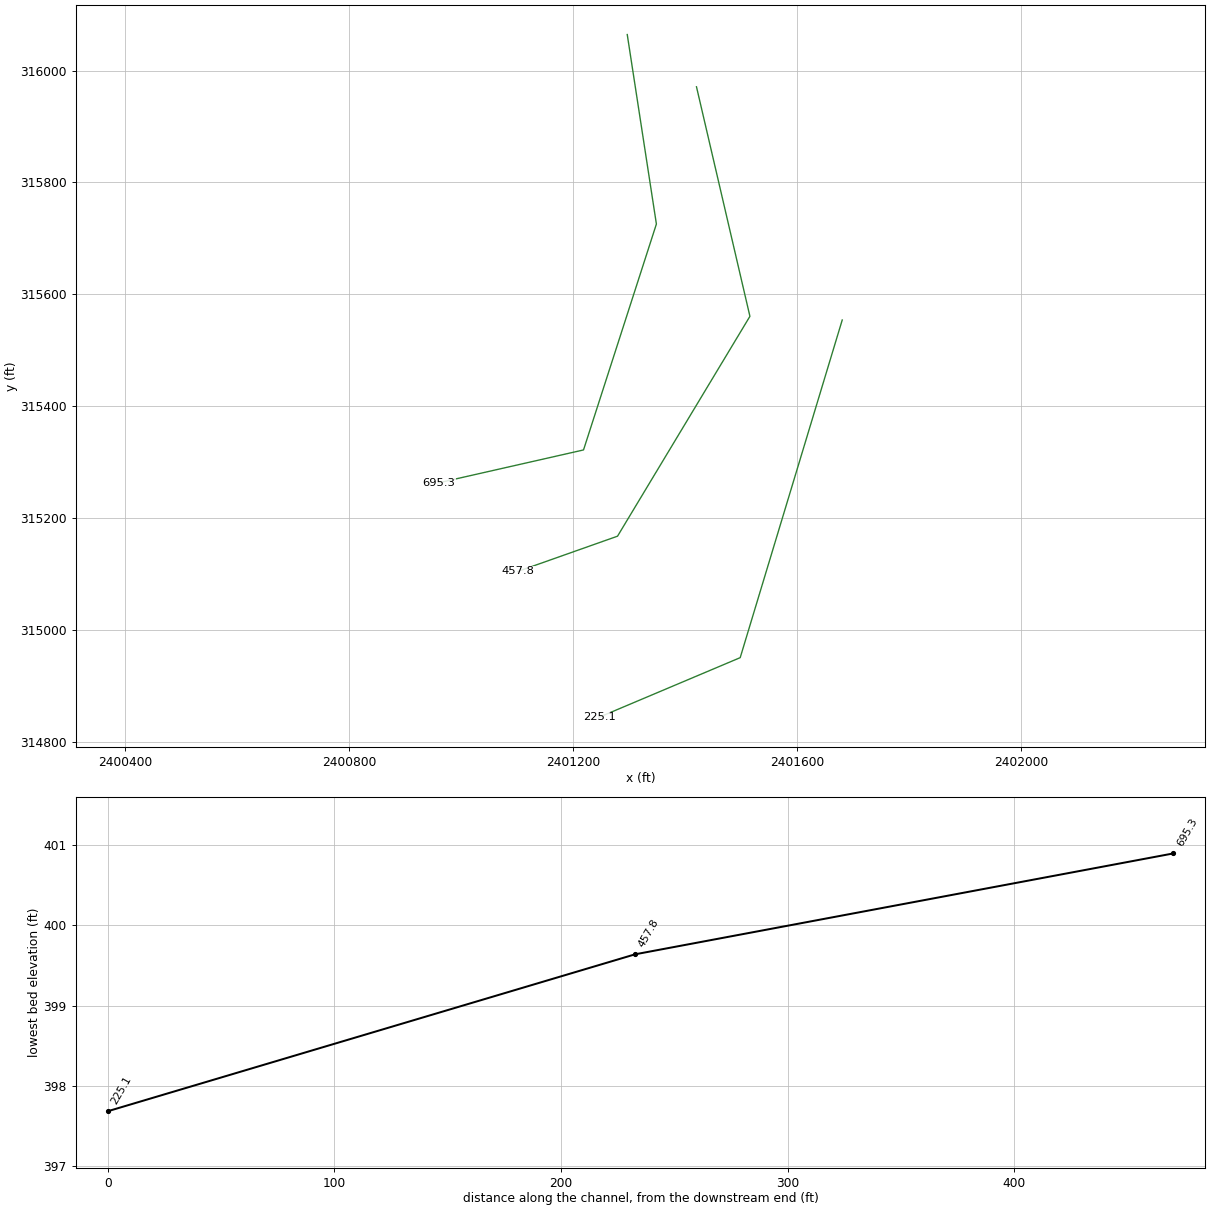
HEC-RAS study MIDDLECRK1.prj: MIDDLECRK1

--- MIDDLECRK1.g01 (geometry) --- (continued)

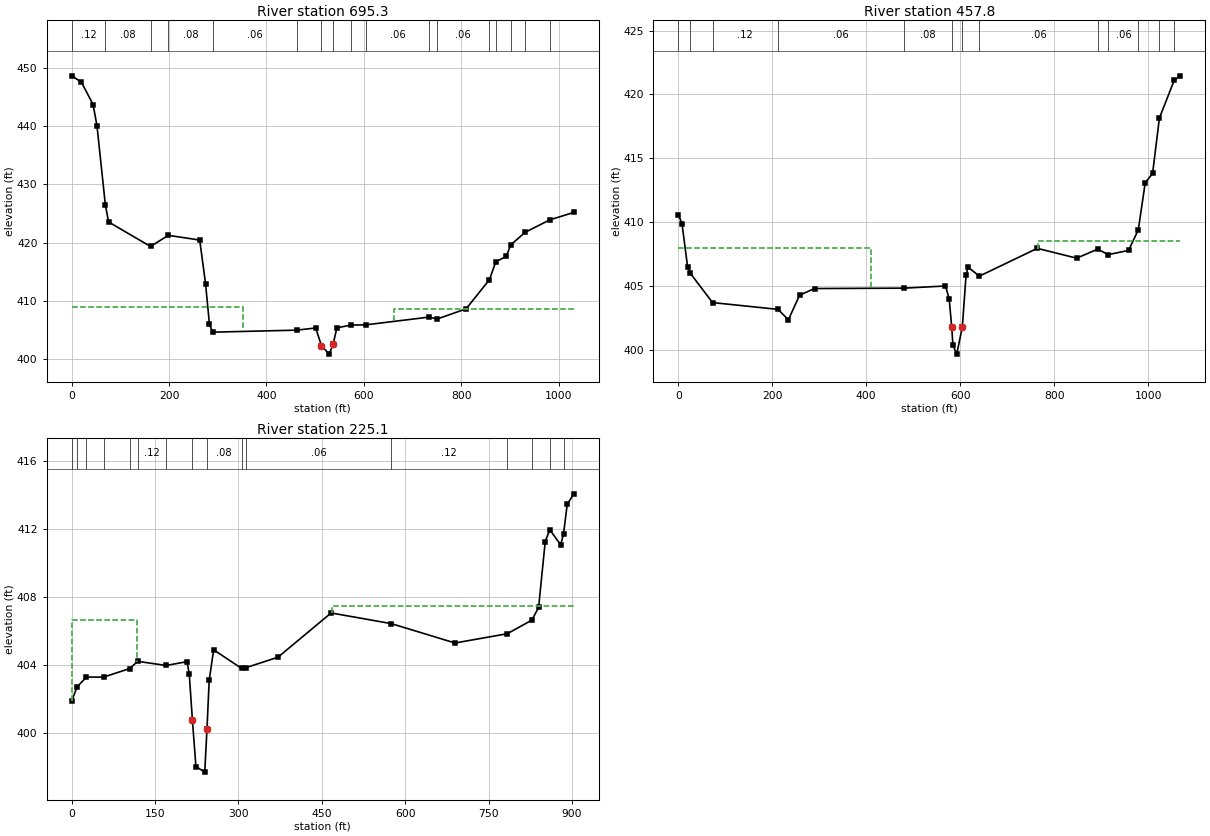
Type RM Length L Ch R = 1 ,695.3   ,244.7,237.5,228.3
XS GIS Cut Line= 4
     2401296.759      316064.244     2401348.842      315725.703
     2401218.634      315322.057     2400960.387      315263.463
#Sta/Elev= 30
       0  448.58    19.9  447.48    43.8  443.66    51.8  440.01   69.06426.4222
    75.7  423.54  161.77419.3482  198.48421.2548   262.9  420.44   274.8  412.99
   282.8  406.07  289.18404.6626  462.18405.0078   501.1  405.38     513  402.35
   528.8   400.9   536.8  402.56   544.7  405.41   573.4 405.865  604.25405.9219
  734.77407.2493  750.05406.8987   810.1  408.66  858.16 413.658  871.04416.7065
   893.1  417.67  901.42419.5867   931.8421.7885   982.5423.9138  1031.5  425.18
#Mann= 17 ,-1 , 0
       0     .12       0   69.06     .08       0  161.77    .016       0
  198.48     .08       0  289.18     .06       0  462.18     .08       0
     513    .045       0   536.8     .08       0   573.4     .12       0
  604.25     .06       0  734.77     .12       0  750.05     .06       0
  858.16     .12       0  871.04    .016       0  901.42     .12       0
   931.8     .06       0   982.5     .12       0
#XS Ineff= 2 , 0
           351.7  409.04  662.54          408.61
Permanent Ineff=
       F       F
Bank Sta=513,536.8
XS Rating Curve= 0 ,0
Exp/Cntr=0.3,0.1

Type RM Length L Ch R = 1 ,457.8   ,225.5,232.7,239.7
XS GIS Cut Line= 4
     2401420.457      315970.928     2401515.943      315560.772
     2401279.398      315167.977     2401101.446      315105.043
#Sta/Elev= 30
       0  410.58       8  409.87    19.9  406.48   25.87405.9686   72.99  403.68
  212.38403.1472   234.4  402.33   258.2  404.26     290  404.78  480.42404.8112
   568.6  404.98   576.6  403.97   581.9  401.77   584.6  400.33   592.6  399.64
   604.5  401.75   612.5  405.83   616.5  406.46  640.77405.7511     764  407.93
   847.8  407.16  892.28407.8624  915.24407.4378   958.3  407.77  979.03409.3868
   993.7  413.07  1009.4   413.8 1023.91418.1403  1055.4421.1008  1068.4  421.45
#Mann= 13 ,-1 , 0
       0     .08       0   25.87    .016       0   72.99     .12       0
  212.38     .06       0  480.42     .08       0   581.9    .045       0
   604.5     .12       0  640.77     .06       0  892.28     .12       0
  915.24     .06       0  979.03    .016       0 1023.91     .12       0
  1055.4     .06       0
#XS Ineff= 2 , 0
          411.15  407.97  766.56          408.53
Permanent Ineff=
       F       F
Bank Sta=581.9,604.5
XS Rating Curve= 0 ,0
Exp/Cntr=0.3,0.1

Type RM Length L Ch R = 1 ,225.1   ,200.8,225.1,249
XS GIS Cut Line= 3
     2401680.873      315554.262     2401498.582      314950.963
     2401246.846      314844.626
#Sta/Elev= 30
       0  401.89    9.72402.7103   26.43403.2812   57.11403.2798  104.28403.7831
  118.48404.2095  169.75 403.965   207.4  404.19   211.4  403.47  217.07 400.754
   223.4  398.01   239.3  397.68   243.3  400.22   247.3  403.09   255.3  404.89
  305.46403.7952  313.73403.8397     371  404.45   466.7  407.06  574.99406.4315
   689.6  405.29  783.47405.8331  827.97406.6385   840.1  407.39     852  411.27
  860.24411.9612   879.8  411.08   884.9 411.717   891.6  413.46   903.5  414.08
#Mann= 16 ,-1 , 0
       0     .12       0    9.72     .08       0   26.43     .06       0
   57.11     .12       0  104.28     .06       0  118.48     .12       0
  169.75     .08       0  217.07    .045       0   243.3     .08       0
  305.46     .12       0  313.73     .06       0  574.99     .12       0
  783.47     .06       0  827.97     .08       0  860.24    .016       0
   884.9     .06       0
#XS Ineff= 2 , 0
          117.65  406.64  467.49          407.49
Permanent Ineff=
       F       F
Bank Sta=217.07,243.3
XS Rating Curve= 0 ,0
Exp/Cntr=0.3,0.1
LCMann Table=0

Chan Stop Cuts=-1
Use User Specified Reach Order=0
Composite Channel Slope=5